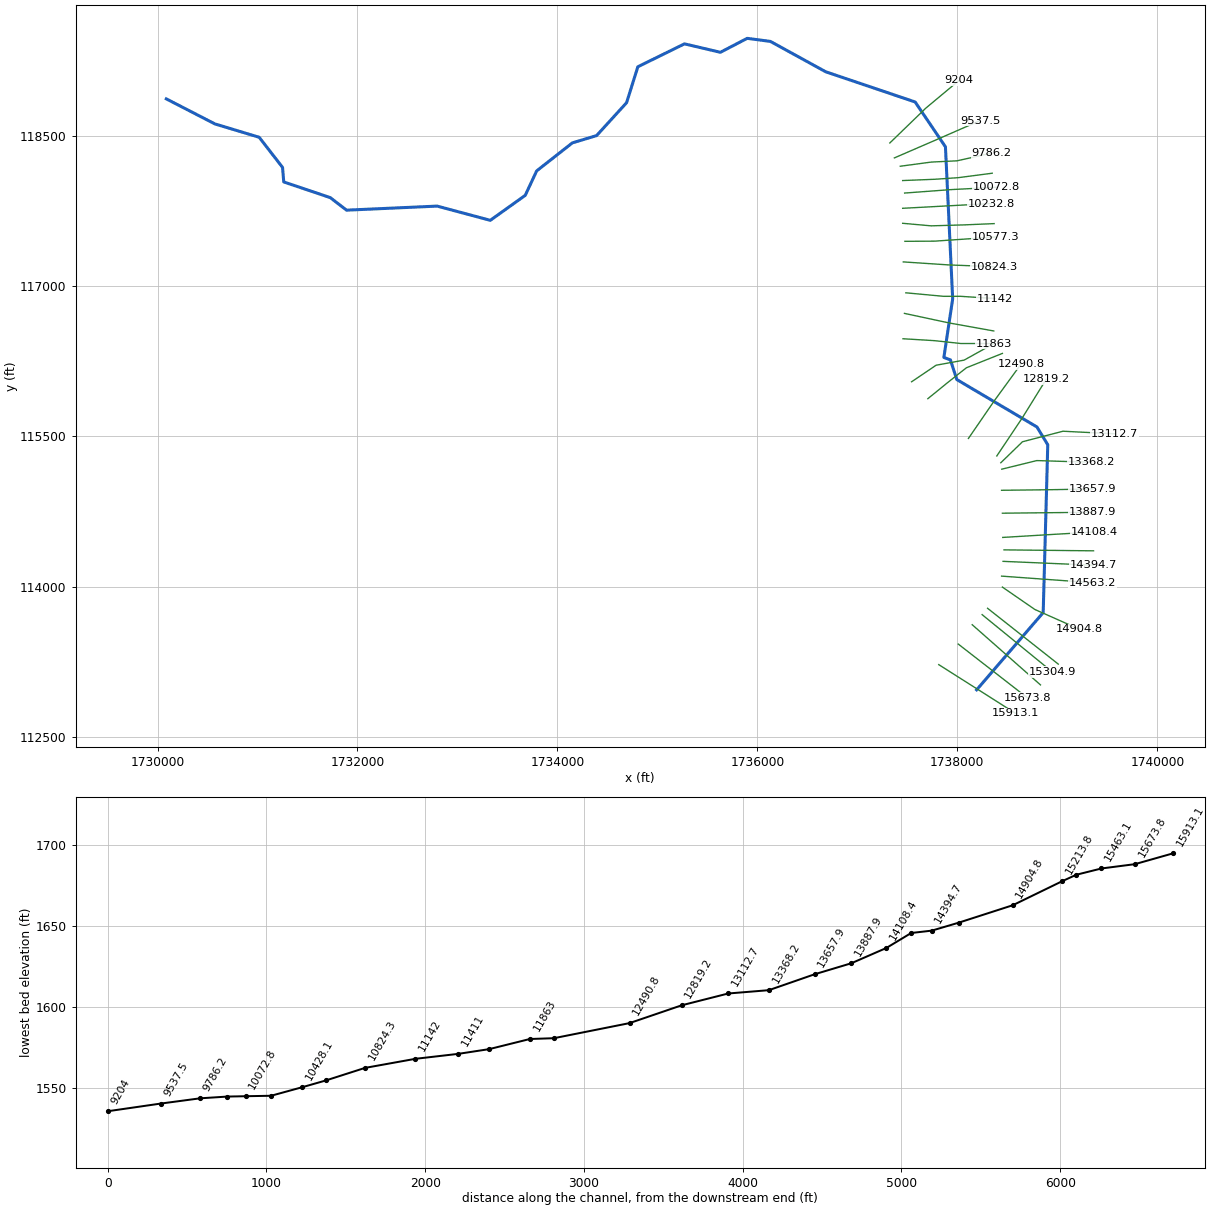
--- Hite Fork.prj (project) ---

Proj Title=Hite Fork
Current Plan=p01
Default Exp/Contr=0,0
English Units
Geom File=g01
Flow File=f01
Plan File=p01
BEGIN DESCRIPTION:
END DESCRIPTION:
DSS Export Rating Curves= 0
DSS Export Rating Curve Sorted= 0
DSS Export Volume Flow Curves= 0
DXF OffsetX= 0
DXF OffsetY= 0
DXF ScaleX= 0
DXF ScaleY= 0

--- Hite Fork.p01 (plan) ---

Plan Title=Floodplain
Program Version=4.00
Geom File=g01
Flow File=f01
K Sum by GR=0
Std Step Tol=0.01
Critical Tol=0.01
Num of Std Step Trials=20
Max Error Tol=0.3
Flow Tol Ratio=0.001
Split Flow NTrial=30
Split Flow Tol=0.02
Split Flow Ratio=0.02
Log Output Level=0
Friction Slope Method=1
Unsteady Friction Slope Method=2
Unsteady Bridges Friction Slope Method=1
Global Log Level=0
CheckData=False
Run HTab=0
Run UNet=0
Run PostProcess=0
UNET Theta=0
UNET Theta Warmup=0
UNET ZTol=0
UNET ZSATol=0
UNET MxIter=0
UNET MaxInSteps=0
UNET DtIC=0
UNET DtMin=0
UNET MaxCRTS=0
UNET WFStab=0
UNET SFStab=0
UNET WFX=0
UNET SFX=0
UNET DSS MLevel=0
UNET DZMax Abort=0
UNET Convert EG Bridges=0
UNET Use Existing IB Tables=0
UNET Froude Limit=0
UNET Froude Power=0
Write IC File=0
Echo Input=False
Echo Output=False
Write Detailed=0

--- Hite Fork.f01 (steady flow) ---

Flow Title=NFF Regression Equation
Program Version=4.00
Number of Profiles=1
Profile Names=P100yr
River Rch & RM=Hite Fork,Main      ,15913.1
     557
River Rch & RM=Hite Fork,Main      ,15213.8
577.2459
River Rch & RM=Hite Fork,Main      ,14904.8
693.9693
River Rch & RM=Hite Fork,Main      ,13112.7
722.1826
River Rch & RM=Hite Fork,Main      ,12819.2
843.3197
River Rch & RM=Hite Fork,Main      ,12014.3
884.4005
River Rch & RM=Hite Fork,Main      ,10577.3
960.8159
River Rch & RM=Hite Fork,Main      ,8058.5
1065.258
River Rch & RM=Hite Fork,Main      ,5951.5
1180.829
River Rch & RM=Hite Fork,Main      ,2355.1
1295.932
River Rch & RM=Hite Fork,Main      ,2049.8
2048.053
River Rch & RM=Hite Fork,Main      ,1755
2049.213
River Rch & RM=Hite Fork,Main      ,1438.6
2661.515
River Rch & RM=Hite Fork,Main      ,255.6
2672.691
Boundary for River Rch & Prof#=Hite Fork,Main      ,1
Up Type=0
Dn Type=3
Dn Slope=0.014185

--- Hite Fork.g01 (geometry) ---

Geom Title=USGS 10m DEM
Program Version=4.00

River Reach=Hite Fork       ,Main
Reach XY= 30
      1738192.76      112967.736     1738858.463       113739.91
     1738904.272      115417.159     1738796.185      115594.801
     1737994.331      116068.902     1737930.836      116265.376
     1737865.095      116289.763     1737953.206      116875.252
     1737880.849      118394.771     1737577.882      118842.974
     1736683.643      119144.731       1736130.2      119448.387
      1735898.03        119479.1     1735629.929      119339.569
     1735270.753      119423.921      1734804.33      119194.874
     1734691.528      118835.907     1734391.981      118507.201
     1734149.464      118434.334     1733792.359      118154.272
     1733677.835      117909.608     1733328.539      117660.259
     1732797.045      117802.372     1731890.748      117761.768
     1731727.613        117887.3     1731262.463      118043.888
     1731250.567      118189.218     1731016.799      118490.343
      1730574.62      118623.472     1730087.952      118874.074

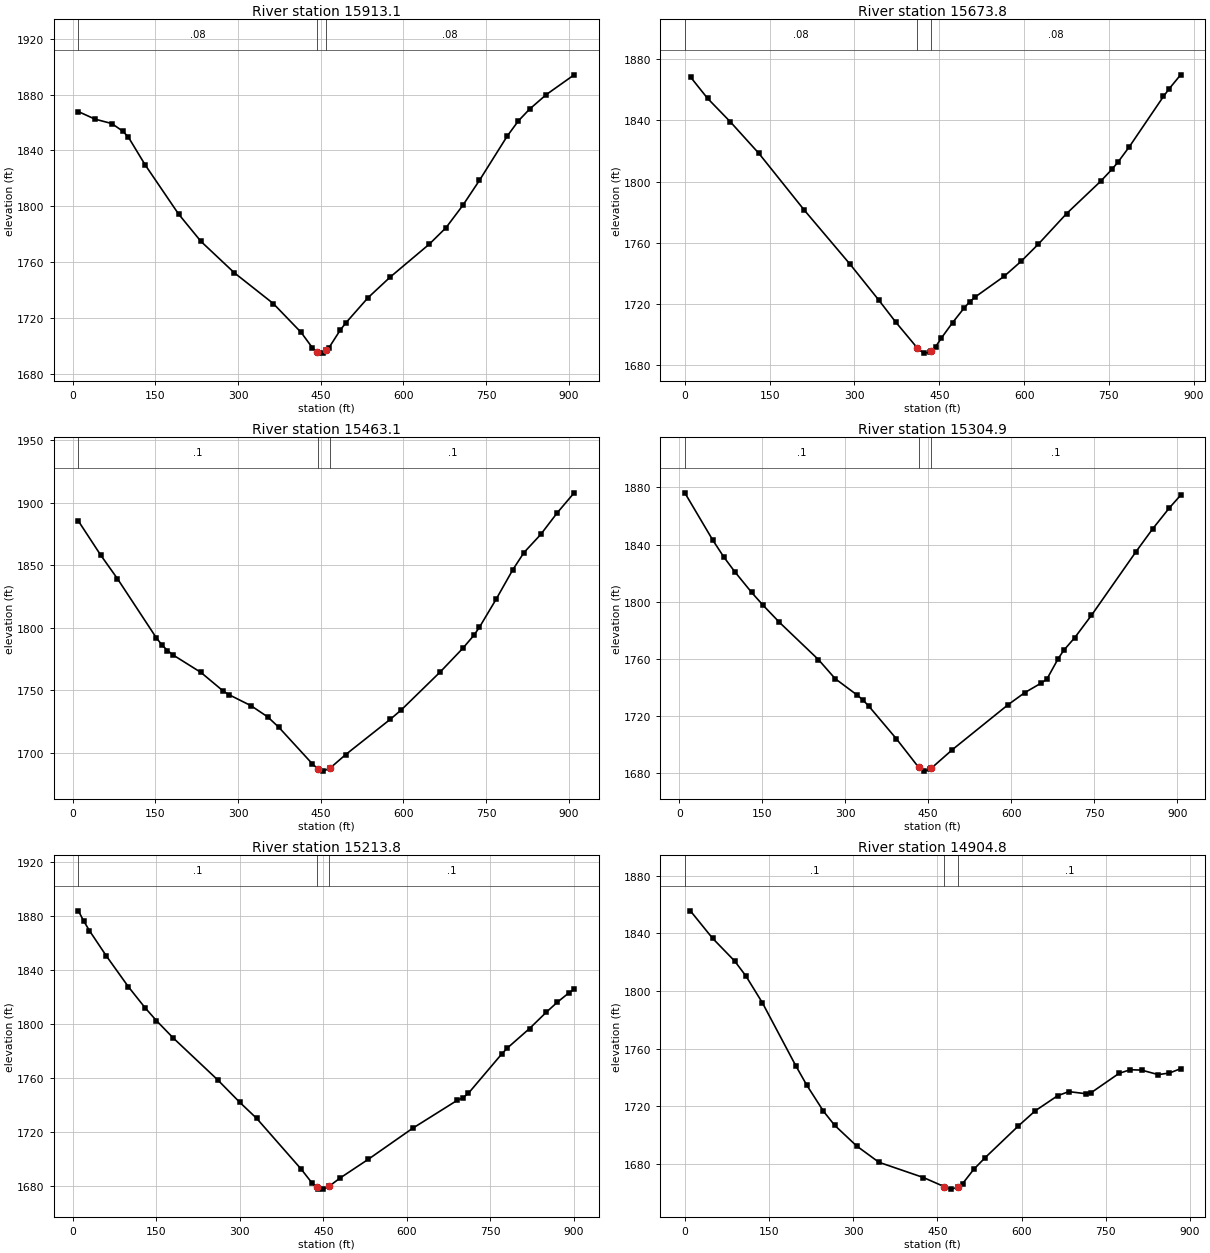
Type RM Length L Ch R = 1 ,15913.1 ,241.9,239.3,236.7
XS GIS Cut Line= 3
     1737813.833      113219.806     1738198.115      112976.182
     1738582.396      112732.557
#Sta/Elev= 30
    10.1 1867.86    40.4 1862.43    70.8 1859.28      91 1853.74   101.1  1849.4
   131.4 1829.63   192.1 1794.33   232.6 1774.77   293.2 1752.23     364 1730.15
   414.6 1709.42   434.8 1698.49   442.5 1695.56   444.9 1694.64     455 1694.62
  459.64 1696.51   465.1 1698.57   485.3 1711.04   495.4 1716.22   535.9 1734.38
   576.3 1749.23   647.1 1772.78   677.4 1784.57   707.8 1800.53   738.1 1818.52
   788.7 1850.38   808.9 1861.25   829.1 1869.61   859.4 1880.03     910 1894.22
#Mann= 3 , 0 , 0
    10.1     .08       0   442.5    .045       0  459.64     .08       0
Bank Sta=442.5,459.64
XS Rating Curve= 0 ,0
Exp/Cntr=0.3,0.1

Type RM Length L Ch R = 1 ,15673.8 ,212.4,210.7,209
XS GIS Cut Line= 2
     1738008.651      113425.583     1738700.917      112887.707
#Sta/Elev= 30
    10.1 1868.34    40.3 1854.38    80.6 1839.03     131 1818.45   211.6 1781.25
   292.2 1746.06   342.6 1722.82   372.8 1708.33   410.7 1691.54   413.1 1690.52
   423.2 1687.99   433.3 1688.57   435.7 1689.41   443.4 1692.09   453.4  1697.7
   473.6 1707.97   493.8 1717.42   503.8 1721.55   513.9 1724.79   564.3 1738.07
   594.5 1747.89   624.7 1759.02   675.1 1779.15   735.6 1800.35   755.7 1808.25
   765.8 1812.68     786 1822.79   846.4 1855.68   856.5 1860.68   876.7 1869.77
#Mann= 3 , 0 , 0
       0     .08       0   410.7    .045       0   435.7     .08       0
Bank Sta=410.7,435.7
XS Rating Curve= 0 ,0
Exp/Cntr=0.3,0.1

Type RM Length L Ch R = 1 ,15463.1 ,157.1,158.2,159.2
XS GIS Cut Line= 3
     1738148.523      113618.685      1738489.92      113317.897
     1738831.316      113017.109
#Sta/Elev= 30
    10.1 1885.27    50.6 1858.03    80.9 1839.24   151.7 1791.84   161.8 1786.18
   171.9 1781.72     182 1778.17   232.6 1764.21     273 1749.35   283.1  1746.5
   323.6 1737.59   353.9 1728.64   374.1 1720.31   434.8 1691.15   444.9  1687.1
     455 1685.33   467.5 1687.93   495.4 1698.57   576.3 1726.75   596.6 1734.39
   667.3 1764.76   707.8 1783.43     728 1793.87   738.1 1800.34   768.4 1822.72
   798.8 1846.39     819 1860.05   849.3 1874.46   879.7    1892     910 1907.74
#Mann= 3 , 0 , 0
    10.1      .1       0   444.9    .045       0   467.5      .1       0
Bank Sta=444.9,467.5
XS Rating Curve= 0 ,0
Exp/Cntr=0.3,0.1

Type RM Length L Ch R = 1 ,15304.9 ,90.6,91.1,91.5
XS GIS Cut Line= 2
     1738247.707      113719.422     1738949.933      113146.684
#Sta/Elev= 30
    10.1 1876.17    60.4 1843.26    80.5 1831.33   100.7 1820.83   130.9 1806.49
     151 1797.74   181.2 1785.53   251.7 1759.45   281.9 1746.14   322.2 1734.51
   332.3 1731.11   342.3  1727.1   392.7 1703.99   432.9 1684.03     443 1681.47
   453.1  1682.7   455.5 1683.46   493.4  1696.4     594 1727.82   624.3 1736.33
   654.5 1743.12   664.5 1745.84   684.7    1760   694.7 1765.87   714.9 1774.87
   745.1  1790.5   825.6 1835.01   855.8 1851.03     886 1865.69   906.2 1874.48
#Mann= 3 , 0 , 0
    10.1      .1       0   432.9    .045       0   455.5      .1       0
Bank Sta=432.9,455.5
XS Rating Curve= 0 ,0
Exp/Cntr=0.3,0.1

Type RM Length L Ch R = 1 ,15213.8 ,302.1,309.1,316
XS GIS Cut Line= 2
      1738302.29      113782.735     1739009.496      113224.938
#Sta/Elev= 30
      10 1883.81      20 1876.02      30 1869.07      60 1850.53   100.1 1827.37
   130.1  1811.8   150.1 1802.46   180.1 1789.65   260.2 1758.48   300.2 1741.69
   330.3 1729.89   410.3 1692.24   430.3 1681.65   437.9 1678.63   440.3 1677.68
   450.4 1677.39   460.4 1679.46   480.4 1685.68   530.4 1699.38   610.5  1722.5
   690.5 1743.22   700.6 1745.09   710.6 1748.43   770.6 1777.63   780.6 1782.01
   820.6 1796.53   850.7 1808.61   870.7 1816.11   890.7 1822.77   900.7 1825.53
#Mann= 3 , 0 , 0
      10      .1       0   437.9    .045       0   460.4      .1       0
Bank Sta=437.9,460.4
XS Rating Curve= 0 ,0
Exp/Cntr=0.3,0.1

Type RM Length L Ch R = 1 ,14904.8 ,332.1,341.5,351
XS GIS Cut Line= 3
     1738450.246      113994.848     1738775.721       113770.62
     1739221.959      113573.001
#Sta/Elev= 30
     9.9 1855.68    49.4 1836.68    88.9 1820.83   108.7 1810.59   138.3 1791.86
   197.6 1748.34   217.4 1734.72     247 1716.73   266.8 1707.02   306.3 1692.57
   345.8 1681.32   425.1 1670.73   462.4 1664.38   474.9 1662.69   487.4 1664.12
   494.8 1666.46   514.8 1676.42   534.7 1684.38   594.4 1706.56   624.3    1717
   664.2 1727.47   684.1  1730.3     714 1728.88   723.9 1729.56   773.7 1742.99
   793.6 1745.48   813.6 1745.24   843.4  1742.1   863.4 1743.21   883.3 1746.21
#Mann= 3 , 0 , 0
       0      .1       0   462.4    .045       0   487.4      .1       0
Bank Sta=462.4,487.4
XS Rating Curve= 0 ,0
Exp/Cntr=0.3,0.1

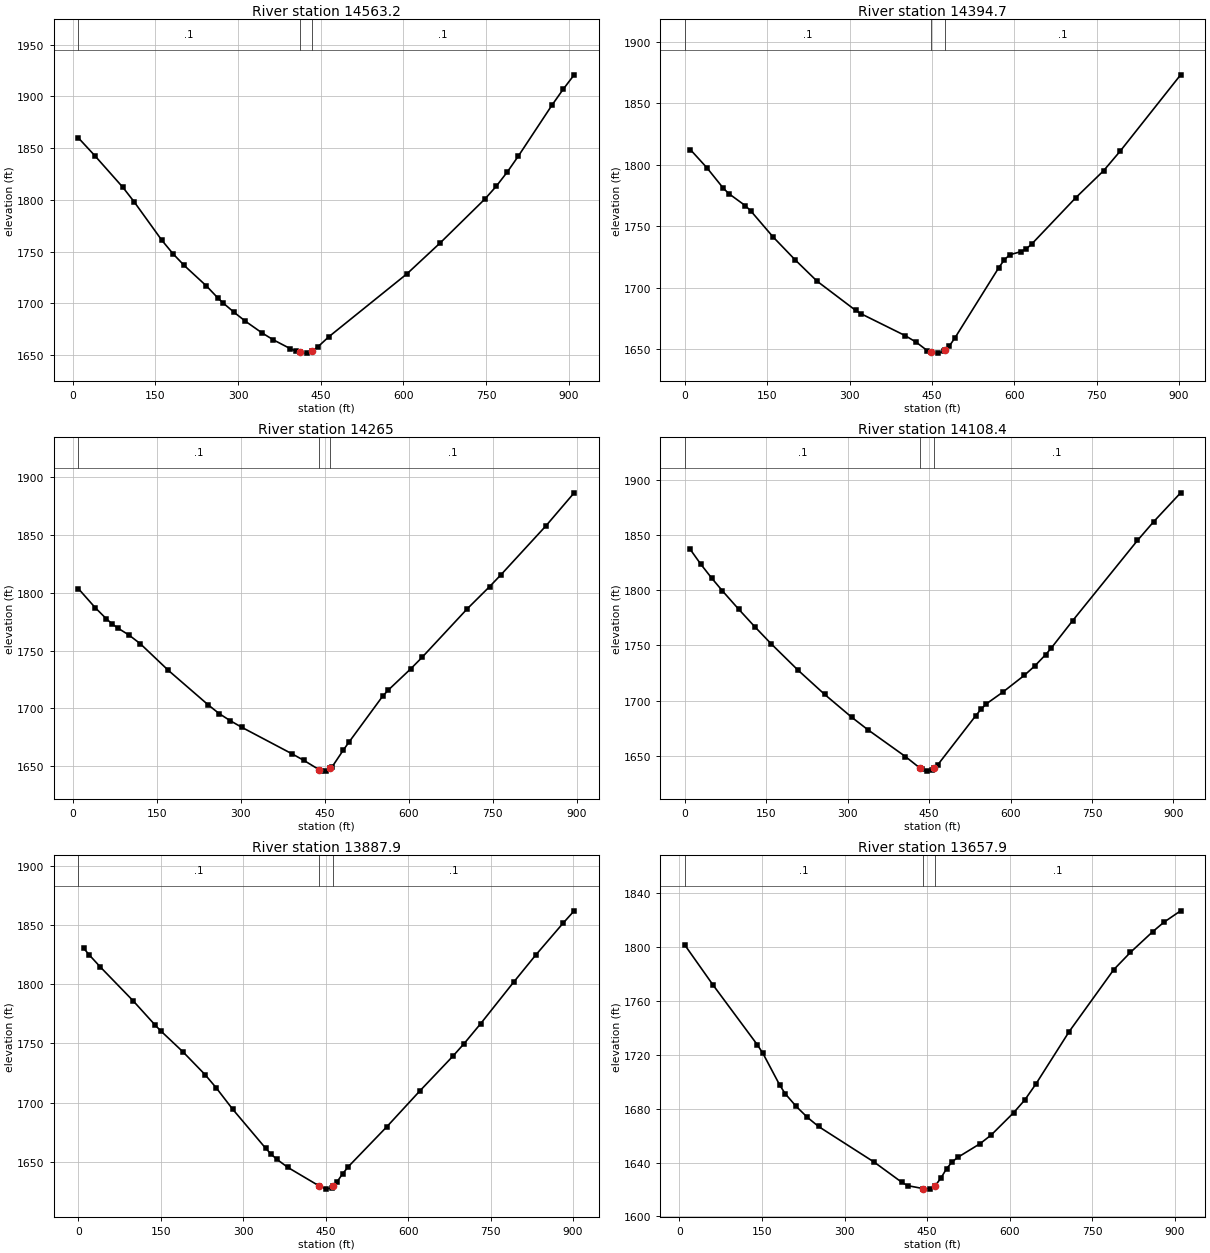
Type RM Length L Ch R = 1 ,14563.2 ,167.9,168.5,169.1
XS GIS Cut Line= 3
      1738442.32      114104.292     1738896.133      114071.454
     1739349.947      114038.617
#Sta/Elev= 30
    10.1 1859.87    40.4 1842.43      91 1812.03   111.2 1798.22   161.8 1760.85
     182 1747.85   202.2 1736.63   242.7 1716.75   262.9 1705.45     273 1700.29
   293.2 1691.17   313.4 1682.71   343.8 1671.34     364 1664.77   394.3 1656.37
   404.4 1653.96   412.2 1652.66   424.7 1651.92   434.8 1653.71   444.9 1658.04
   465.1 1667.88   606.7  1728.6   667.3 1758.62   748.2 1800.89   768.4 1812.96
   788.7 1826.92   808.9 1842.41   869.6 1891.34   889.8 1906.61     910 1920.74
#Mann= 3 , 0 , 0
    10.1      .1       0   412.2    .045       0   434.8      .1       0
Bank Sta=412.2,434.8
XS Rating Curve= 0 ,0
Exp/Cntr=0.3,0.1

Type RM Length L Ch R = 1 ,14394.7 ,128.8,129.7,130.6
XS GIS Cut Line= 2
      1738456.98      114251.919     1739359.018       114213.67
#Sta/Elev= 30
      10 1812.34    40.1 1797.61    70.2 1780.89    80.3 1776.49   110.3 1766.73
   120.4 1762.36   160.5 1741.49   200.6 1722.92   240.8 1705.47     311 1681.78
     321 1678.99   401.3 1661.25   421.3 1655.93   441.4 1649.11     449 1647.67
   461.5 1647.05   471.5 1648.54     474 1649.59   481.5 1652.72   491.6 1659.24
   571.8 1716.48   581.8 1722.84   591.9 1726.96   611.9  1729.4     622 1731.75
     632 1735.77   712.2 1773.37   762.4 1795.07   792.5  1810.9   902.8 1872.99
#Mann= 3 , 0 , 0
       0      .1       0     449    .045       0     474      .1       0
Bank Sta=449,474
XS Rating Curve= 0 ,0
Exp/Cntr=0.3,0.1

Type RM Length L Ch R = 1 ,14265   ,154.6,156.6,158.5
XS GIS Cut Line= 2
     1738466.543      114366.666     1739362.205      114357.104
#Sta/Elev= 30
    10.1 1803.68    40.3 1787.15    60.4  1777.4    70.4 1773.15    80.5 1769.55
   100.6 1763.46   120.8 1755.93   171.1 1732.77   241.5 1703.22   261.7 1695.39
   281.8 1689.17   301.9 1683.59   392.5 1660.38   412.6 1654.99   440.4 1646.78
   442.8 1646.13   452.9 1645.59  460.47 1648.15     463 1649.04   483.1  1663.6
   493.1 1670.44   553.5 1710.38   563.6 1715.76   603.9 1734.25     624 1744.12
   704.5 1786.08   744.8 1805.49   764.9 1815.66   845.4 1858.11   895.7 1886.66
#Mann= 3 , 0 , 0
    10.1      .1       0   440.4    .045       0  460.47      .1       0
Bank Sta=440.4,460.47
XS Rating Curve= 0 ,0
Exp/Cntr=0.3,0.1

Type RM Length L Ch R = 1 ,14108.4 ,221.9,220.6,219.2
XS GIS Cut Line= 3
     1738453.793      114490.975     1738908.964      114518.438
     1739365.392      114545.161
#Sta/Elev= 30
     9.9 1836.91    29.7 1823.28    49.6 1810.82    69.4 1799.27    99.1 1782.82
   128.9 1766.91   158.6  1751.7   208.2  1727.8   257.7 1705.66   307.3 1685.12
     337 1673.85   406.4 1649.51   433.6 1638.92   436.2 1637.96   446.1 1636.36
     456 1637.71   458.6 1638.85   465.9 1642.07   535.5 1686.26   545.5 1692.23
   555.4  1697.2   585.2 1707.59     625 1722.83   644.8 1731.53   664.7 1741.73
   674.7 1747.49   714.4 1772.41   833.7 1844.91   863.5 1861.84   913.2 1887.97
#Mann= 3 , 0 , 0
       0      .1       0   433.6    .045       0   458.6      .1       0
Bank Sta=433.6,458.6
XS Rating Curve= 0 ,0
Exp/Cntr=0.3,0.1

Type RM Length L Ch R = 1 ,13887.9 ,230,230,230.2
XS GIS Cut Line= 2
     1738450.606      114733.218     1739352.643       114742.78
#Sta/Elev= 30
      10 1830.06      20 1824.51    40.1 1814.37   100.2 1785.63   140.3  1765.1
   150.3 1760.34   190.4 1742.78   230.5 1723.61   250.6 1712.59   280.6 1694.51
   340.8 1661.44   350.8  1656.4   360.8 1652.28   380.9 1645.36   438.5 1629.54
     451 1626.95   461.1 1628.19   463.5 1629.44   471.1 1633.38   481.1 1640.05
   491.1 1645.85   561.3 1679.61   621.4 1709.86   681.6 1739.21   701.6  1749.6
   731.7 1766.42   791.8 1801.49   831.9 1824.34     882  1851.4   902.1  1861.8
#Mann= 3 , 0 , 0
       0      .1       0   438.5    .045       0   463.5      .1       0
Bank Sta=438.5,463.5
XS Rating Curve= 0 ,0
Exp/Cntr=0.3,0.1

Type RM Length L Ch R = 1 ,13657.9 ,290.9,289.7,288.4
XS GIS Cut Line= 3
     1738442.228      114962.169     1738897.196      114967.459
     1739352.139        114975.1
#Sta/Elev= 30
    10.1 1801.69    60.7 1772.33   141.6 1727.61   151.7 1721.29     182 1697.86
   192.1 1691.25   212.3  1681.7   232.6 1673.57   252.8 1666.78   353.9 1640.26
   404.4 1625.16   414.6  1622.8   442.5 1620.62     455 1620.21  463.65 1622.22
   475.2  1628.6   485.3 1635.49   495.4 1640.48   505.6 1643.85     546    1654
   566.2 1660.45   606.7 1676.94   626.9 1686.37   647.1 1698.22   707.8 1737.38
   788.7 1783.42     819 1796.26   859.4 1811.61   879.7 1818.64     910  1827.1
#Mann= 3 , 0 , 0
    10.1      .1       0   442.5    .045       0  463.65      .1       0
Bank Sta=442.5,463.65
XS Rating Curve= 0 ,0
Exp/Cntr=0.3,0.1

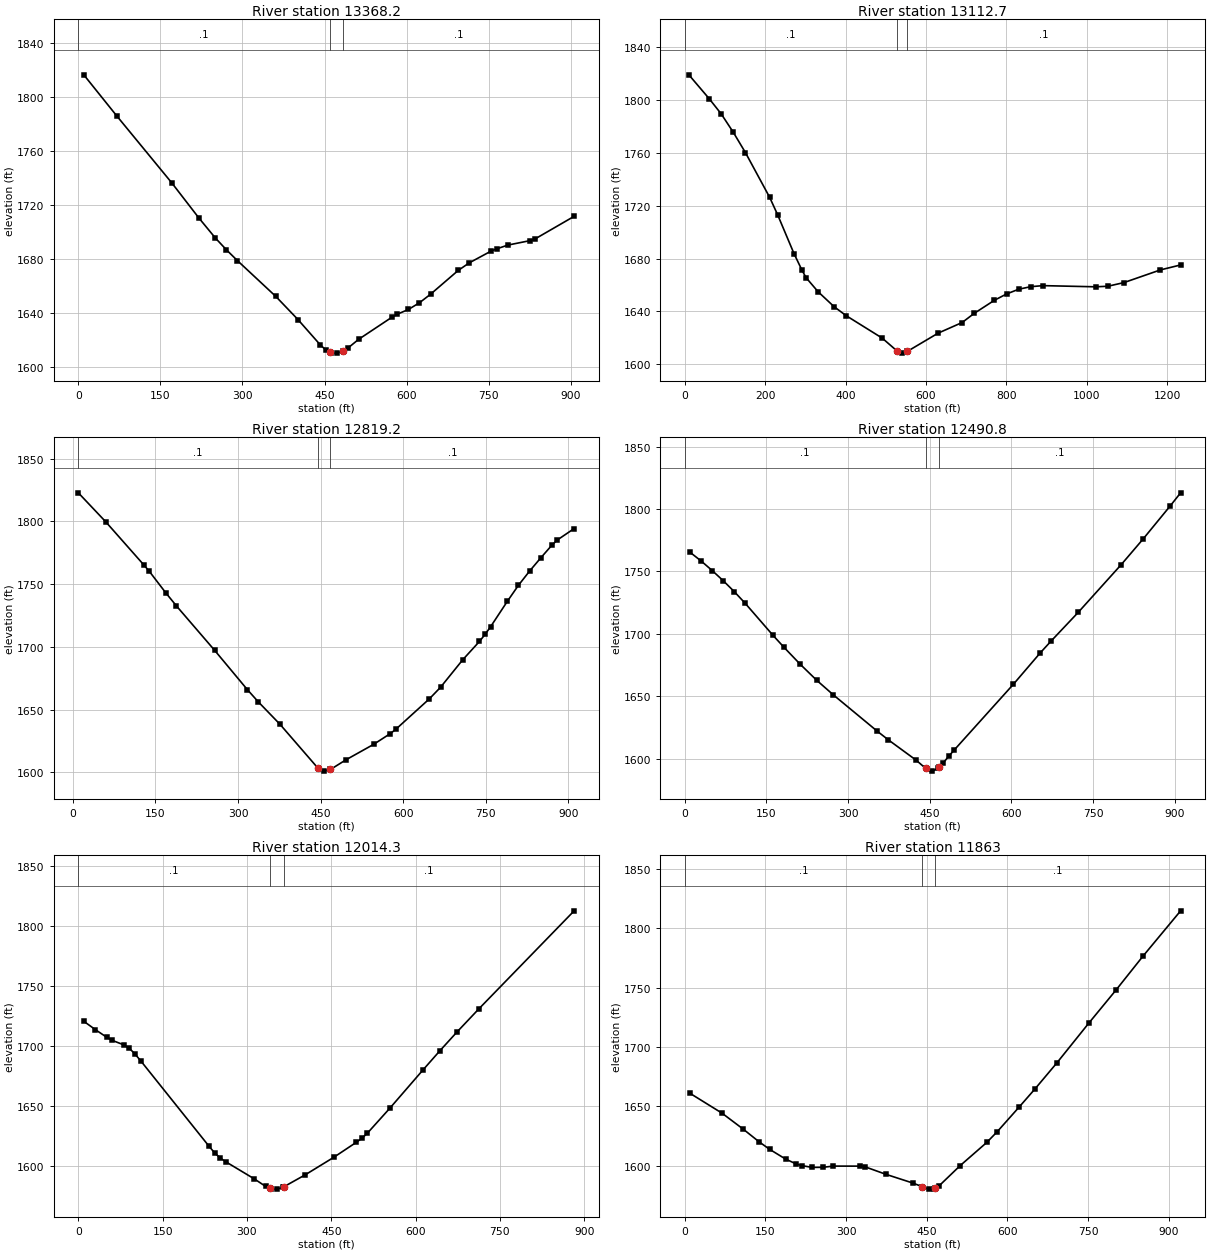
Type RM Length L Ch R = 1 ,13368.2 ,247.6,255.5,263.4
XS GIS Cut Line= 4
     1738444.231      115173.081     1738794.846      115259.141
      1739097.65      115249.578     1739339.893      115243.204
#Sta/Elev= 30
      10 1816.28    70.2  1785.9   170.5  1736.5   220.6 1710.23   250.7 1695.44
   270.8 1686.77   290.8 1678.81     361  1652.3   401.4 1635.23   441.8 1616.69
   451.9 1612.87   459.6 1611.18     462 1610.65   472.1 1610.37   484.6    1612
   492.3 1613.97   512.5 1620.62   573.1 1636.91   583.2 1639.21   603.4 1642.68
   623.6 1647.65   643.8 1653.95   694.3 1671.53   714.5 1677.15   754.9 1685.96
   764.9 1687.55   785.1 1690.31   825.5 1693.59   835.6 1695.04   906.3 1711.59
#Mann= 3 , 0 , 0
       0      .1       0   459.6    .045       0   484.6      .1       0
Bank Sta=459.6,484.6
XS Rating Curve= 0 ,0
Exp/Cntr=0.3,0.1

Type RM Length L Ch R = 1 ,13112.7 ,273.3,293.5,314.6
XS GIS Cut Line= 4
     1738434.577      115237.199     1738651.412      115447.198
     1739056.214      115552.382     1739569.387      115526.883
#Sta/Elev= 30
    10.1 1819.15    60.4 1801.18    90.6 1789.56   120.7 1775.61   150.9 1760.24
   211.3 1726.28   231.4 1712.87   271.7 1683.77   291.8 1671.03   301.9 1665.46
   331.7 1654.84   371.6 1643.49   401.4 1636.74   491.1 1619.74   528.4 1609.91
   540.9 1608.33   553.4 1609.58   630.5 1623.48   690.2 1631.52   720.1 1638.42
   770.5 1648.37   800.7 1653.14   830.9 1656.73   861.1 1658.67   891.4 1659.46
  1022.3 1658.57  1052.6 1658.98  1092.9 1661.77  1183.5 1671.36  1233.9 1675.13
#Mann= 3 , 0 , 0
       0      .1       0   528.4    .045       0   553.4      .1       0
Bank Sta=528.4,553.4
XS Rating Curve= 0 ,0
Exp/Cntr=0.3,0.1

Type RM Length L Ch R = 1 ,12819.2 ,328.8,328.5,326.4
XS GIS Cut Line= 3
     1738394.804      115305.555     1738648.151      115683.894
     1738888.071      116070.431
#Sta/Elev= 30
     9.9 1822.71    59.4 1799.76   128.7 1765.35   138.6 1760.29   168.3 1743.29
   188.1  1732.6   257.4 1697.27   316.8 1665.98   336.5 1656.32   376.1 1638.35
   445.4 1603.24   455.3 1601.05   467.8 1602.38   495.8 1610.03   546.3 1622.41
   576.6 1630.99   586.8 1634.51   647.4 1658.63   667.6 1667.81   708.1 1689.81
   738.4 1704.38   748.5 1709.96   758.6 1716.09     789 1736.32   809.2 1749.11
   829.4  1760.4   849.6 1770.87   869.8 1780.99   879.9 1785.21   910.3 1794.25
#Mann= 3 , 0 , 0
     9.9      .1       0   445.4    .045       0   467.8      .1       0
Bank Sta=445.4,467.8
XS Rating Curve= 0 ,0
Exp/Cntr=0.3,0.1

Type RM Length L Ch R = 1 ,12490.8 ,485.3,476.4,468.3
XS GIS Cut Line= 3
     1738110.696      115480.304     1738368.487      115855.228
      1738636.98       116223.65
#Sta/Elev= 30
    10.1 1765.22    30.3 1758.29    50.6 1750.63    70.8  1742.5      91  1733.8
   111.2 1724.38   161.8 1698.95     182 1689.36   212.3 1675.56   242.7  1662.7
     273 1651.12   353.9 1621.94   374.1 1615.08   424.7 1598.94   442.5 1592.31
   444.9 1591.45     455 1590.08   464.9 1592.22   467.5 1593.38   474.8 1596.63
   484.7 1601.92   494.6 1606.82   603.7 1659.67   653.2 1684.89     673  1694.3
   722.6 1717.17   801.9 1755.55   841.5 1775.75   891.1 1802.14   910.9 1812.99
#Mann= 3 , 0 , 0
       0      .1       0   442.5    .045       0   467.5      .1       0
Bank Sta=442.5,467.5
XS Rating Curve= 0 ,0
Exp/Cntr=0.3,0.1

Type RM Length L Ch R = 1 ,12014.3 ,164.9,151.3,137.8
XS GIS Cut Line= 4
     1737704.752      115877.498     1737908.746      116043.244
     1738090.428      116186.677     1738450.606      116330.111
#Sta/Elev= 30
    10.1 1720.55    30.3 1713.73    50.5 1707.37    60.7  1704.7    80.9 1701.03
      91 1698.04   101.1 1693.25   111.2 1687.61   232.5 1616.52   242.6 1610.92
   252.7 1606.62   262.8 1603.45   313.2 1589.27   333.3 1583.02   340.9 1581.55
   343.4 1581.06   353.4 1580.79   363.5 1582.25   365.9 1582.83   403.7 1592.74
   454.1 1607.21   494.3 1619.75   504.3 1623.14   514.2 1627.43     554 1648.16
   613.6 1680.41   643.4 1696.25   673.2 1711.58     713  1731.3     882 1812.76
#Mann= 3 , 0 , 0
       0      .1       0   340.9    .045       0   365.9      .1       0
Bank Sta=340.9,365.9
XS Rating Curve= 0 ,0
Exp/Cntr=0.3,0.1

Type RM Length L Ch R = 1 ,11863   ,265.2,256.7,247.2
XS GIS Cut Line= 4
     1737542.194      116046.431     1737787.624      116212.176
     1738068.116      116263.175      1738366.19      116428.888
#Sta/Elev= 30
     9.9 1660.88    69.1 1644.28   108.6 1630.81   138.2 1620.13   157.9 1613.76
   187.6 1605.58   207.3 1601.46   217.2 1600.12   236.9 1598.58   256.7 1598.65
   276.4 1599.68   325.6 1599.65   335.5 1599.04   374.8 1592.65     424 1585.44
   440.9 1582.49   453.4 1580.29   463.3 1580.34   465.9 1581.07   473.1 1583.09
   512.4 1600.15   561.6 1619.56   581.2 1628.67   621.4 1649.12   651.5  1664.7
   691.6 1686.28   751.8  1720.2   801.9 1747.77   852.1 1776.31   922.3 1814.57
#Mann= 3 , 0 , 0
       0      .1       0   440.9    .045       0   465.9      .1       0
Bank Sta=440.9,465.9
XS Rating Curve= 0 ,0
Exp/Cntr=0.3,0.1

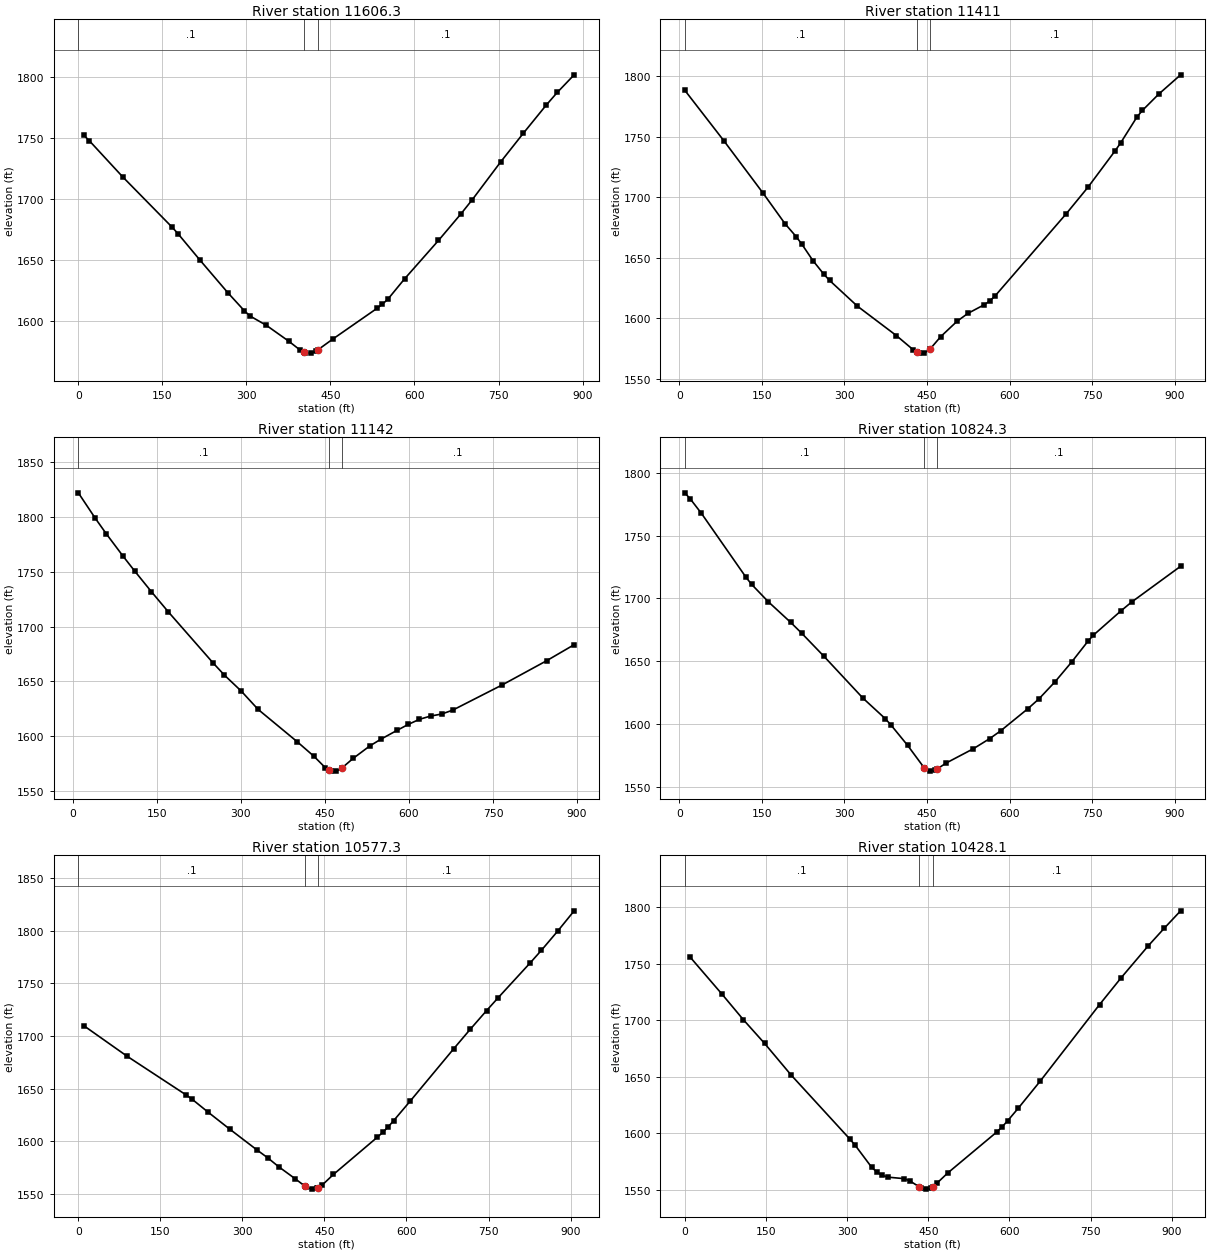
Type RM Length L Ch R = 1 ,11606.3 ,198.2,195.4,193
XS GIS Cut Line= 4
     1737456.134      116476.732     1737771.687      116457.607
     1738036.242       116428.92     1738339.046       116428.92
#Sta/Elev= 30
     9.9 1752.34    19.8 1747.81      79 1718.42   167.9 1676.89   177.8 1671.84
   217.3 1650.09   266.7 1623.57   296.4 1608.69   306.3 1604.49   335.8 1596.74
   375.3 1583.91     395 1576.87   402.2 1575.14   404.8 1574.51   414.7 1574.05
   424.5 1575.73   427.2 1576.61   454.1 1585.52     533 1610.67   542.8 1614.11
   552.7 1618.31   582.2 1634.78   642.8 1666.26   683.2 1688.18   703.4 1699.79
   753.8 1730.55   794.2 1753.97   834.6 1776.76   854.8 1787.43     885 1801.85
#Mann= 3 , 0 , 0
       0      .1       0   402.2    .045       0   427.2      .1       0
Bank Sta=402.2,427.2
XS Rating Curve= 0 ,0
Exp/Cntr=0.3,0.1

Type RM Length L Ch R = 1 ,11411   ,263.2,269,274.3
XS GIS Cut Line= 3
     1737470.931      116730.094     1737915.819       116634.96
     1738363.981      116554.618
#Sta/Elev= 30
    10.1 1788.24    80.9 1746.62   151.6 1703.66   192.1    1678   212.3 1667.36
   222.4 1661.25   242.6 1647.63   262.9  1636.1     273 1631.16   323.5 1609.92
   394.3  1585.6   424.6 1573.98   432.3  1571.9   434.7 1571.25   444.8 1571.13
   454.9 1574.22   474.7 1584.74   504.4 1597.44   524.2 1603.99   553.9 1611.14
   563.8  1614.2   573.7 1618.51   702.4 1686.13     742 1708.12   791.5 1738.33
   801.4 1744.78   831.1 1766.23     841 1771.65   870.7 1785.14   910.3 1801.01
#Mann= 3 , 0 , 0
    10.1      .1       0   432.3    .045       0   454.9      .1       0
Bank Sta=432.3,454.9
XS Rating Curve= 0 ,0
Exp/Cntr=0.3,0.1

Type RM Length L Ch R = 1 ,11142   ,319.5,317.7,316.7
XS GIS Cut Line= 4
      1737484.82      116935.719     1737864.122      116900.657
     1738033.055      116900.657     1738377.295      116878.345
#Sta/Elev= 30
      10 1822.28    40.1 1799.15    60.1  1784.7    90.2 1764.17   110.3 1751.01
   140.3 1732.03   170.4 1713.66   250.6 1666.83   270.7 1655.77   300.7 1641.21
   330.8 1624.47   400.8 1594.84   430.6 1581.57   450.5 1571.34   457.9 1568.96
   460.4 1568.16   470.4 1568.09   480.3 1570.93   500.2 1579.63     530 1591.05
   549.9 1597.26   579.4  1605.5   599.1 1610.84   618.8 1615.43   638.6 1618.38
   658.3 1620.23     678 1623.77   766.7 1646.91   845.5 1668.87   894.8 1683.57
#Mann= 3 , 0 , 0
      10      .1       0   457.9    .045       0   480.3      .1       0
Bank Sta=457.9,480.3
XS Rating Curve= 0 ,0
Exp/Cntr=0.3,0.1

Type RM Length L Ch R = 1 ,10824.3 ,243.3,247,249.9
XS GIS Cut Line= 3
     1737459.307      117244.531     1737913.287      117214.627
     1738368.154      117197.081
#Sta/Elev= 30
    10.1 1784.11    20.2 1779.17    40.4 1767.69   121.3 1716.79   131.4 1711.21
   161.8 1697.33   202.2 1680.99   222.4 1672.27   262.9 1653.84   333.6 1620.57
   374.1 1604.23   384.2 1599.31   414.5 1583.06   444.9 1564.99     455 1562.49
   464.9 1563.27   467.5 1563.98   484.7 1568.97   534.1 1580.36   563.8 1588.43
   583.6 1594.61   633.1 1612.27   652.9 1619.98   682.6 1633.83   712.3 1649.33
   741.9 1665.89   751.8 1670.74   801.3 1689.89   821.1 1697.08   910.2 1725.63
#Mann= 3 , 0 , 0
    10.1      .1       0   444.9    .045       0   467.5      .1       0
Bank Sta=444.9,467.5
XS Rating Curve= 0 ,0
Exp/Cntr=0.3,0.1

Type RM Length L Ch R = 1 ,10577.3 ,150.3,149.2,148.2
XS GIS Cut Line= 3
     1737475.308      117450.354     1737771.687      117452.079
     1738380.483      117493.515
#Sta/Elev= 30
     9.9 1709.79    88.9 1680.89   197.6  1643.9   207.5 1640.22   237.1 1627.82
   276.6 1611.73   326.4 1591.99   346.4 1584.39   366.4 1575.96   396.4 1564.62
   413.9 1557.72   416.4 1556.75   426.4 1554.74   436.4 1555.37   438.9 1556.24
   446.4 1558.84   466.4 1568.65   546.5 1603.89   556.5 1608.48   566.5 1613.74
   576.5 1619.67   606.5 1638.03   686.5 1687.95   716.5 1706.29   746.5 1724.08
   766.5 1735.63   826.6 1769.55   846.6 1781.21   876.6 1799.53   906.6  1818.7
#Mann= 3 , 0 , 0
       0      .1       0   413.9    .045       0   438.9      .1       0
Bank Sta=413.9,438.9
XS Rating Curve= 0 ,0
Exp/Cntr=0.3,0.1

Type RM Length L Ch R = 1 ,10428.1 ,194.6,195.3,195.9
XS GIS Cut Line= 4
     1737452.946      117630.574     1737736.626      117605.075
     1738068.116      117614.637     1738367.733      117627.387
#Sta/Elev= 30
     9.8 1755.99    68.8 1723.13     108 1700.67   147.3 1679.65   196.4 1651.62
   304.9 1594.94     315  1589.3   345.1 1570.05   355.2 1565.52   365.2  1562.7
   375.3 1561.18   405.4 1559.84   415.5 1557.94   433.1 1552.67   435.6 1551.94
   445.6 1550.57   455.7 1551.84   458.1 1552.76   465.7 1555.68   485.8 1564.81
   576.3 1601.03   586.3 1605.64   596.4 1610.93   616.5 1622.35   656.4 1645.92
   766.4 1713.89   806.4 1737.68   856.4 1765.91   886.4 1781.71   916.3 1796.93
#Mann= 3 , 0 , 0
       0      .1       0   433.1    .045       0   458.1      .1       0
Bank Sta=433.1,458.1
XS Rating Curve= 0 ,0
Exp/Cntr=0.3,0.1

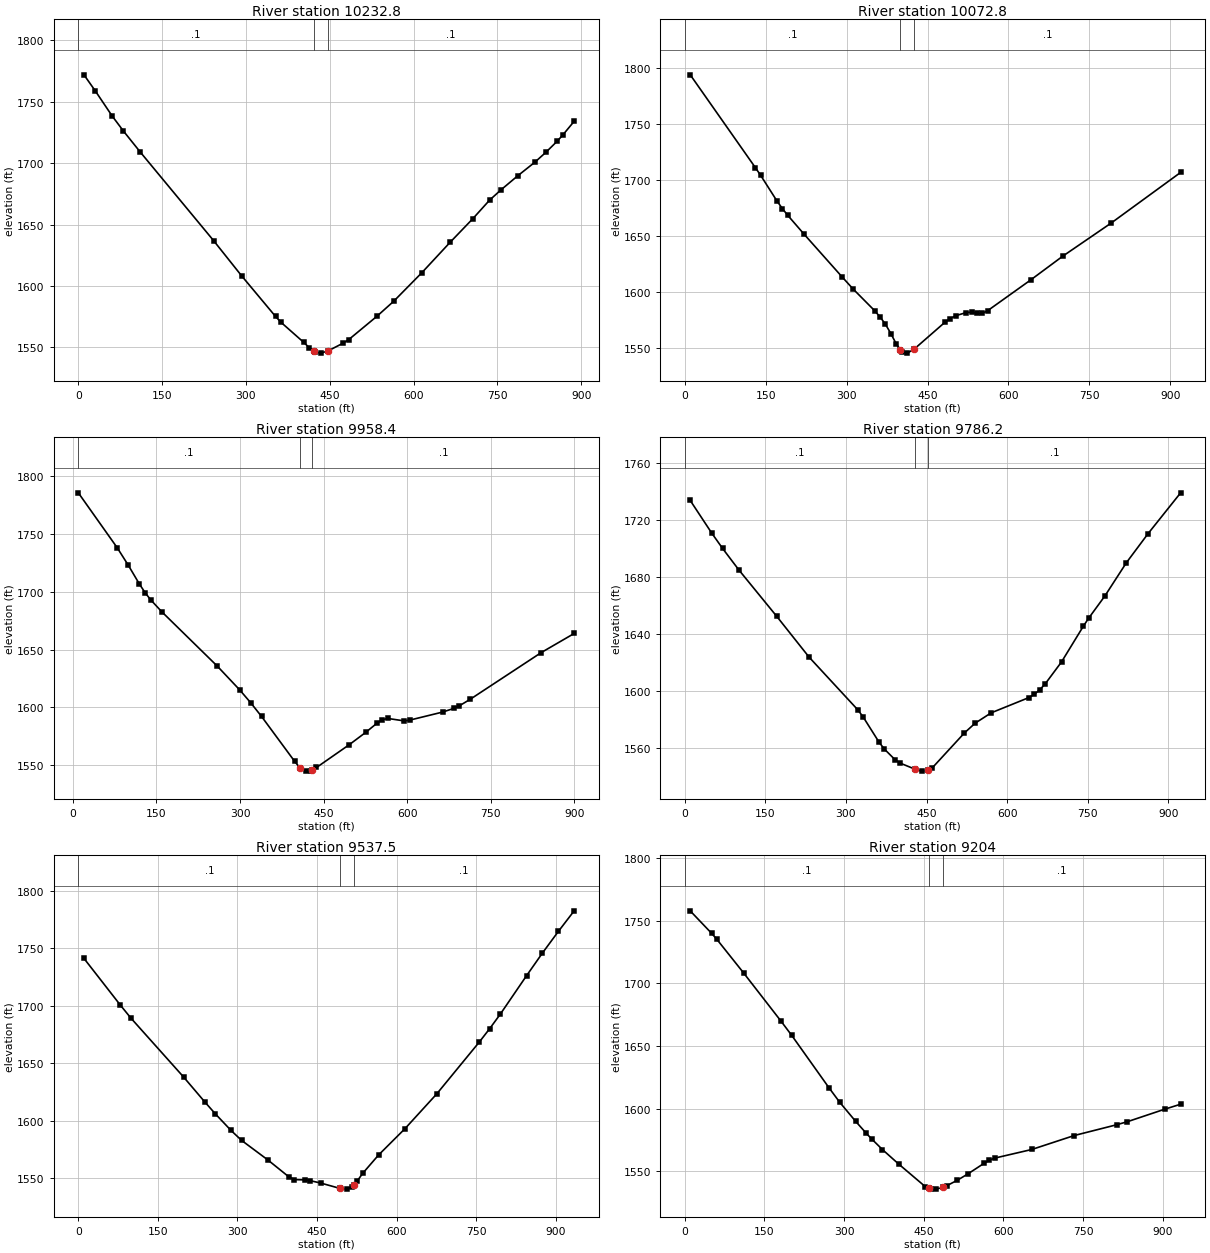
Type RM Length L Ch R = 1 ,10232.8 ,159.4,160,160.6
XS GIS Cut Line= 2
     1737452.946      117780.382     1738339.046      117828.194
#Sta/Elev= 30
    10.1 1771.89    30.3 1758.84    60.5 1738.39    80.7 1726.14   110.9 1708.99
     242 1636.97   292.4 1608.17   352.9 1575.21     363  1570.3   403.4 1554.09
   413.4 1549.71   421.1 1547.13   423.5 1546.33   433.6 1545.33   446.1 1546.94
   473.9 1553.46     484 1556.35   534.5 1575.37   564.7 1587.67   615.1 1610.94
   665.5  1635.6   705.9  1654.7   736.1  1669.9   756.3 1678.19   786.5 1689.72
   816.8 1700.66     837  1708.9   857.1 1717.89   867.2 1722.98   887.4 1734.06
#Mann= 3 , 0 , 0
       0      .1       0   421.1    .045       0   446.1      .1       0
Bank Sta=421.1,446.1
XS Rating Curve= 0 ,0
Exp/Cntr=0.3,0.1

Type RM Length L Ch R = 1 ,10072.8 ,114.7,114.5,114.3
XS GIS Cut Line= 3
     1737472.686      117932.745     1737933.946      117967.137
     1738390.045      117990.751
#Sta/Elev= 30
    10.1 1793.96   130.7 1711.06   140.8 1703.93   170.9 1681.11     181 1674.27
     191 1668.21   221.2 1651.41   291.6 1613.24   311.7 1602.59   351.9 1583.04
     362 1577.41     372 1570.87   382.1 1562.52   392.2 1553.11   399.8 1548.02
   402.2 1546.41   412.3 1545.05   424.8 1548.44   482.4 1572.69   492.3 1575.96
   502.3 1578.52   522.1 1581.36     532 1581.68     542 1580.61   551.9 1580.66
   561.8 1583.11   641.3  1610.5   700.8 1631.77   790.2 1661.28   919.3 1706.67
#Mann= 3 , 0 , 0
       0      .1       0   399.8    .045       0   424.8      .1       0
Bank Sta=399.8,424.8
XS Rating Curve= 0 ,0
Exp/Cntr=0.3,0.1

Type RM Length L Ch R = 1 ,9958.4  ,172.6,172.1,171.7
XS GIS Cut Line= 4
     1737452.946      118057.687     1737771.687      118070.437
     1738007.556      118086.374     1738348.608      118130.998
#Sta/Elev= 30
      10 1785.54    79.7 1738.07    99.7 1722.84   119.6  1706.6   129.6 1699.33
   139.6  1693.1   159.5 1682.77   259.2 1635.68   299.1 1615.28     319  1604.1
   338.7 1592.09   397.8 1553.42   407.6 1547.61   417.5 1544.84   427.3  1545.3
     430 1546.03   437.2 1547.98   496.3 1567.81   525.9  1578.5   545.6 1586.26
   555.4 1589.33   565.2  1590.4   594.7 1588.27   604.5 1588.96   663.5 1595.93
   683.2 1599.04     693 1601.21   712.6 1606.87   840.4 1647.39   899.4 1663.89
#Mann= 3 , 0 , 0
      10      .1       0   407.6    .045       0     430      .1       0
Bank Sta=407.6,430
XS Rating Curve= 0 ,0
Exp/Cntr=0.3,0.1

Type RM Length L Ch R = 1 ,9786.2  ,239.1,248.7,258.5
XS GIS Cut Line= 4
     1737429.213       118200.85     1737738.392      118242.287
     1737996.572      118255.036     1738340.813      118331.534
#Sta/Elev= 30
    10.1 1733.73    50.3 1710.73    70.4 1700.03   100.6 1684.99   171.1 1652.42
   231.4 1623.76   321.9 1586.86   331.8 1581.92   361.7 1564.04   371.6 1559.21
   391.5 1551.76   401.4 1549.31   428.7 1545.11   441.2 1543.76   453.7 1544.57
   461.1 1546.21   520.7 1570.61   540.6 1577.42   570.4 1584.67     641 1595.43
     651 1597.75   661.1 1600.94   671.2 1605.11   701.4 1620.43   741.7 1645.28
   751.8 1651.05     782 1666.64   822.3 1690.14   862.6  1710.5   923.1 1739.08
#Mann= 3 , 0 , 0
       0      .1       0   428.7    .045       0   453.7      .1       0
Bank Sta=428.7,453.7
XS Rating Curve= 0 ,0
Exp/Cntr=0.3,0.1

Type RM Length L Ch R = 1 ,9537.5  ,323.3,333.5,343.5
XS GIS Cut Line= 3
     1737370.073      118283.993     1737834.888       118485.08
     1738227.487       118656.92
#Sta/Elev= 30
     9.9 1741.75    79.4 1700.58    99.3 1689.28   198.6 1638.04   238.3  1616.5
   258.2 1606.11     288 1591.56   307.8 1582.96   357.5 1565.88   397.2 1551.13
   407.1 1548.81     427 1548.57   436.9 1547.91   456.8 1545.85   493.9 1541.08
   506.4 1540.52   516.4  1542.7   518.9    1544   526.4 1547.92   536.3 1554.29
   566.2 1570.24   616.1  1593.2   675.9 1623.42   755.6 1668.24   775.5 1680.06
   795.5 1692.65   845.3 1726.32   875.2 1746.01   905.1 1764.75     935 1782.73
#Mann= 3 , 0 , 0
       0      .1       0   493.9    .045       0   518.9      .1       0
Bank Sta=493.9,518.9
XS Rating Curve= 0 ,0
Exp/Cntr=0.3,0.1

Type RM Length L Ch R = 1 ,9204    ,433.2,444.5,457
XS GIS Cut Line= 3
     1737324.748      118433.369     1737686.293      118783.088
     1738017.118      119058.534
#Sta/Elev= 30
    10.1 1757.96    50.3 1740.09    60.4 1735.17   110.7  1708.4   181.1 1669.92
   201.2 1658.59   271.6 1616.62   291.7 1605.12   321.9 1589.79     342 1580.23
   352.1 1575.73   372.2 1567.35   402.4 1555.92   452.7 1537.82   460.3 1536.45
   462.8    1536   472.8  1535.8   485.3 1537.11   492.9 1538.45     513 1542.86
     533 1547.95   563.1 1556.32   573.1 1558.85   583.1 1560.52   653.2 1567.44
   733.3  1578.6   813.4 1587.22   833.4 1589.65   903.5  1599.6   933.5 1603.58
#Mann= 3 , 0 , 0
       0      .1       0   460.3    .045       0   485.3      .1       0
Bank Sta=460.3,485.3
XS Rating Curve= 0 ,0
Exp/Cntr=0.3,0.1