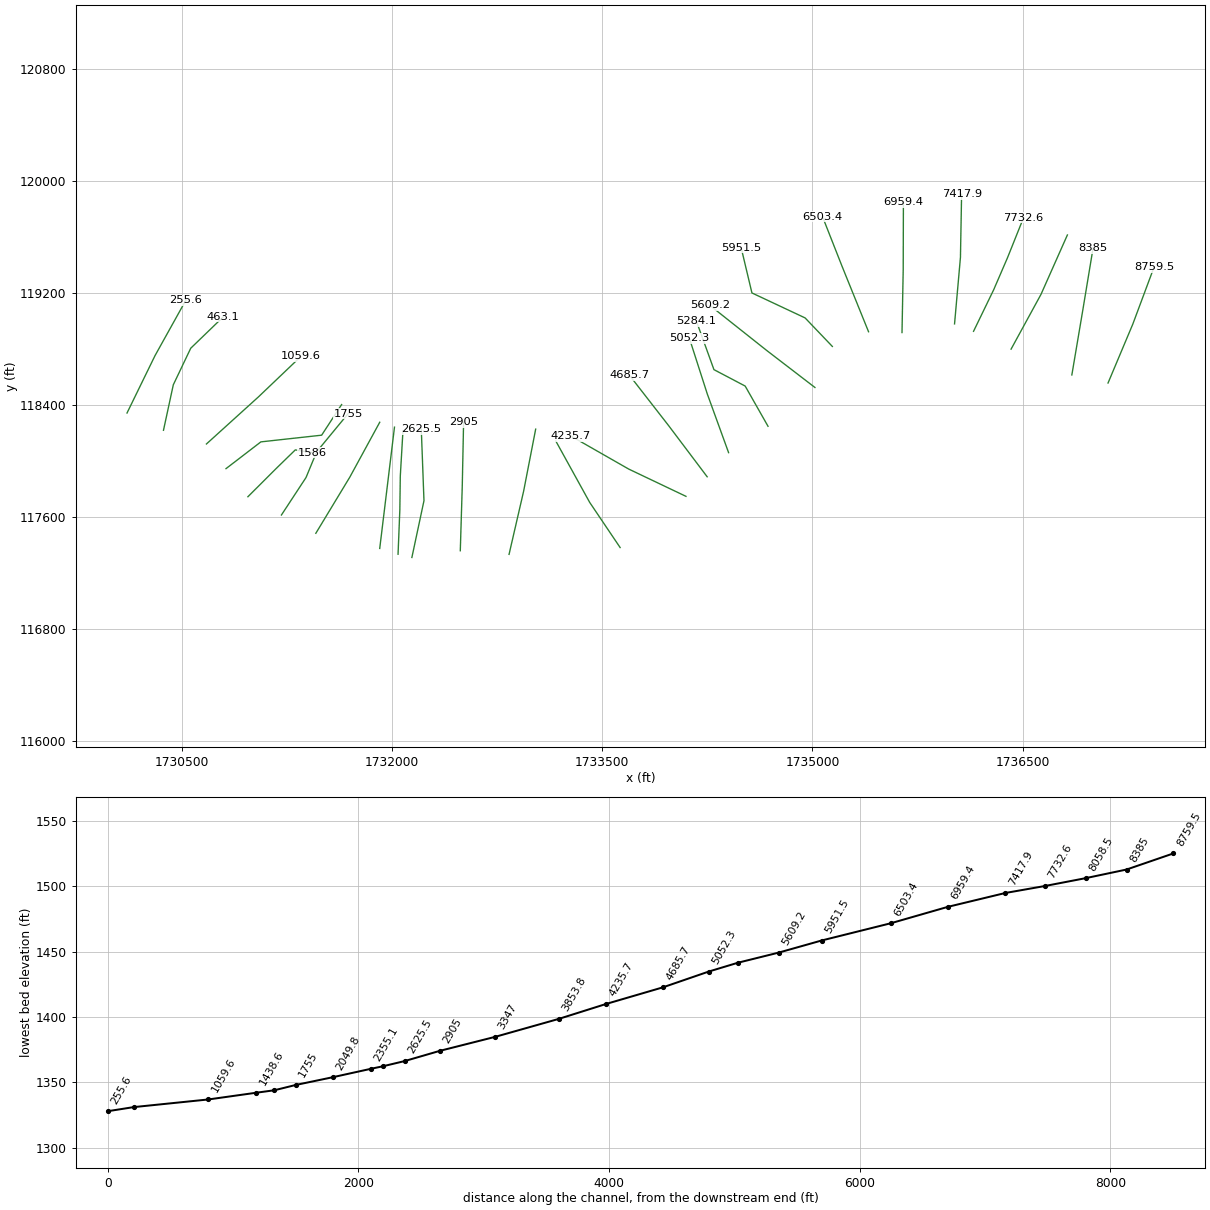
HEC-RAS study Hite Fork.prj: Hite Fork

--- Hite Fork.g01 (geometry) --- (continued)

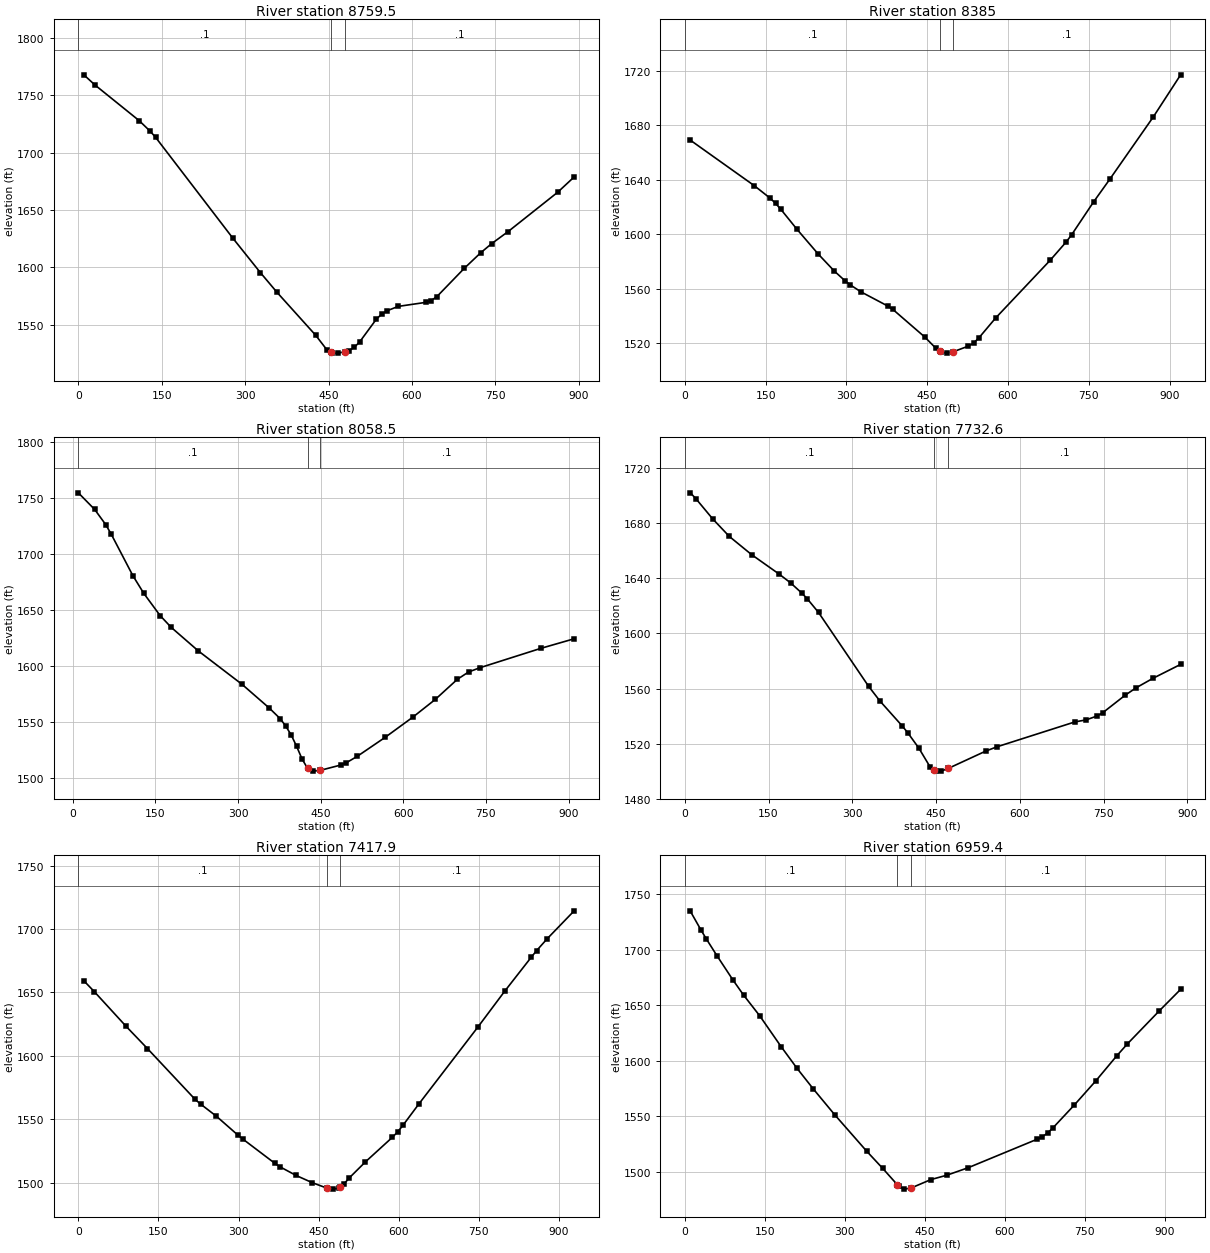
Type RM Length L Ch R = 1 ,8759.5  ,368,374.5,380
XS GIS Cut Line= 3
     1737108.706      118558.111     1737285.332      118979.085
     1737437.009      119386.837
#Sta/Elev= 30
     9.9  1767.9    29.8 1759.07   109.2    1728     129 1718.78   138.9 1713.39
   277.9 1625.31   327.5 1595.21   357.3 1578.06   426.8 1540.62   446.6 1528.15
   453.9 1526.03   456.5 1525.27   466.4 1525.03   478.9 1526.12   486.2 1527.13
   496.1    1530     506  1534.9   535.6 1554.45   545.5 1559.12   555.4 1562.04
   575.2 1565.81   624.6 1569.31   634.5 1570.95   644.4 1574.18   693.8 1598.93
   723.5 1612.59   743.3  1620.6   772.9 1631.13   861.9 1665.39   891.6 1678.78
#Mann= 3 , 0 , 0
       0      .1       0   453.9    .045       0   478.9      .1       0
Bank Sta=453.9,478.9
XS Rating Curve= 0 ,0
Exp/Cntr=0.3,0.1

Type RM Length L Ch R = 1 ,8385    ,335.8,326.5,319.2
XS GIS Cut Line= 3
      1736850.53      118615.845     1736927.971      119074.959
     1737002.055      119523.551
#Sta/Elev= 30
     9.9 1669.12   128.8 1635.67   158.5 1626.39   168.4 1622.65   178.3 1618.24
     208  1603.7   247.7  1585.4   277.4 1572.98   297.2 1565.86   307.1 1562.81
   326.9 1557.69   376.4 1547.34   386.3 1544.75   445.8 1524.38   465.6 1516.44
   473.3 1514.24   475.7 1513.55   485.8  1512.7   498.3 1513.72   526.2 1517.83
   536.3 1520.17   546.4 1524.15   576.7 1538.38   677.8 1580.71   708.1  1594.4
   718.2 1599.71   758.6 1623.62   788.9 1640.39   869.7 1686.16   920.3 1716.98
#Mann= 3 , 0 , 0
       0      .1       0   473.3    .045       0   498.3      .1       0
Bank Sta=473.3,498.3
XS Rating Curve= 0 ,0
Exp/Cntr=0.3,0.1

Type RM Length L Ch R = 1 ,8058.5  ,323.5,325.9,326.3
XS GIS Cut Line= 3
     1736417.038      118800.354     1736630.432      119191.874
     1736818.651      119616.331
#Sta/Elev= 30
     9.9 1754.69    39.6 1739.82    59.5 1726.39    69.4 1717.98     109 1680.63
   128.8 1664.85   158.5    1645   178.4 1634.58   227.9 1613.42   307.2  1583.6
   356.7  1562.4   376.5 1552.92   386.4  1546.4   396.4 1538.43   406.3 1528.18
   416.2 1516.84   426.1 1508.63     436  1506.1   448.5 1506.71   486.3 1511.53
   496.4 1513.55   516.6 1519.39     567 1536.27   617.5 1554.39   657.9 1570.09
   698.2 1588.15   718.4 1594.62   738.6 1598.39   849.7 1615.77   910.2 1624.32
#Mann= 3 , 0 , 0
     9.9      .1       0   426.1    .045       0   448.5      .1       0
Bank Sta=426.1,448.5
XS Rating Curve= 0 ,0
Exp/Cntr=0.3,0.1

Type RM Length L Ch R = 1 ,7732.6  ,306,314.7,325.4
XS GIS Cut Line= 4
     1736149.295       118927.85     1736292.729      119224.279
     1736391.538      119453.773     1736506.285       119740.64
#Sta/Elev= 30
      10 1701.99      20 1697.67    49.9 1683.11    79.8 1670.33   119.7 1657.14
   169.6 1642.85   189.6 1636.62   209.6 1629.24   219.5 1625.04   239.5 1615.22
   329.3 1561.59   349.3 1551.07   389.3 1532.93   399.3 1527.96   419.3 1516.73
   439.2 1503.25   446.7 1501.02   449.2 1500.28   459.2 1500.09   471.7 1502.02
   539.2 1514.65   559.2 1517.75   698.8  1535.8   718.7 1537.25   738.6 1540.11
   748.6 1542.45   788.5 1555.08   808.4 1560.55   838.3 1567.37   888.1 1577.53
#Mann= 3 , 0 , 0
       0      .1       0   446.7    .045       0   471.7      .1       0
Bank Sta=446.7,471.7
XS Rating Curve= 0 ,0
Exp/Cntr=0.3,0.1

Type RM Length L Ch R = 1 ,7417.9  ,454.8,458.5,459.5
XS GIS Cut Line= 3
     1736013.729      118980.863     1736055.826      119456.676
      1736064.05      119907.602
#Sta/Elev= 30
      10 1659.34    29.9 1650.63    89.6 1623.18   129.4 1605.71   218.9 1565.51
   228.9 1561.92   258.7 1552.26   298.5 1537.55   308.5 1534.16   368.2 1515.09
   378.2 1512.27     408 1505.54   437.9 1499.91   465.2 1495.63   477.7 1494.77
   487.7  1495.6   490.2 1496.42   497.7 1498.88   507.7 1503.72   537.8 1516.31
   587.9 1535.55   597.9 1539.84     608 1545.11     638 1562.07   748.3 1622.63
   798.4 1650.85   848.5 1677.87   858.5 1683.08   878.6 1692.55   928.7  1714.4
#Mann= 3 , 0 , 0
       0      .1       0   465.2    .045       0   490.2      .1       0
Bank Sta=465.2,490.2
XS Rating Curve= 0 ,0
Exp/Cntr=0.3,0.1

Type RM Length L Ch R = 1 ,6959.4  ,444.5,456,467.3
XS GIS Cut Line= 3
     1735638.925      118918.897     1735647.552      119370.408
     1735648.872      119849.012
#Sta/Elev= 30
      10 1734.93    30.1 1717.84    40.1 1709.84    60.2 1694.59    90.3 1672.64
   110.4 1658.93   140.5 1640.38   180.6 1612.64   210.7 1592.93   240.8 1574.62
     281 1551.33   341.2 1518.37   371.3 1502.87     399 1487.98   401.4 1486.75
   411.5 1484.18     424 1485.08   461.6 1492.77   491.5 1496.71   531.4 1503.42
     661 1529.14     671 1531.42   680.9 1534.89   690.9 1539.49   730.8 1559.99
   770.7  1581.5   810.5 1604.35   830.5 1615.13   890.3 1644.87   930.2 1664.17
#Mann= 3 , 0 , 0
       0      .1       0     399    .045       0     424      .1       0
Bank Sta=399,424
XS Rating Curve= 0 ,0
Exp/Cntr=0.3,0.1

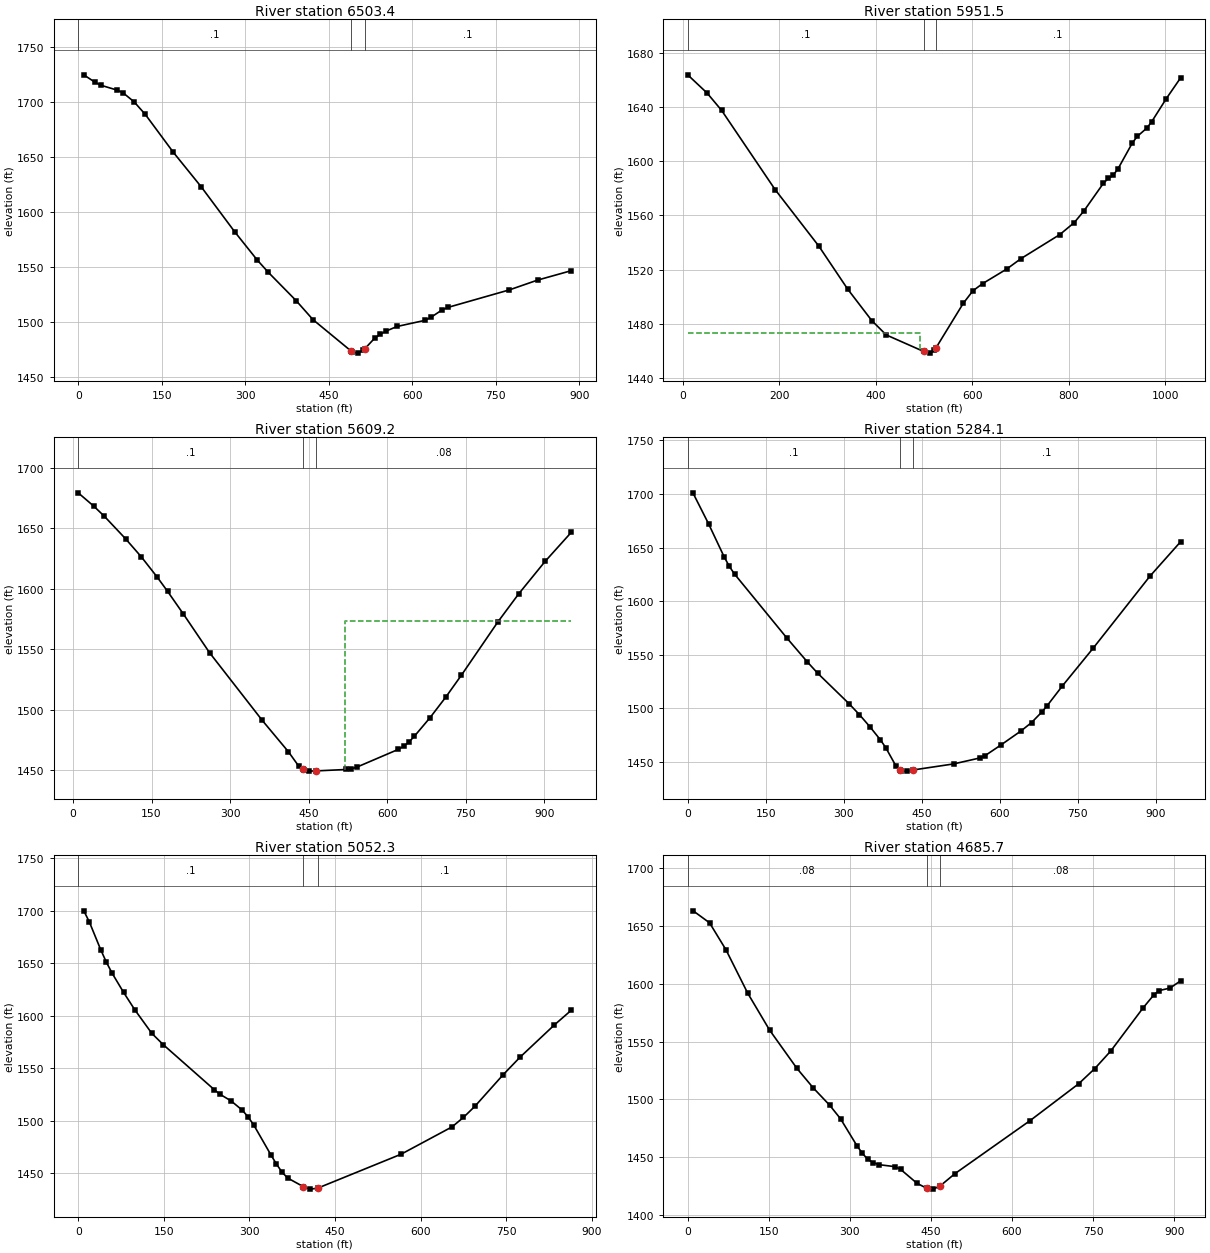
Type RM Length L Ch R = 1 ,6503.4  ,531.2,551.9,572.8
XS GIS Cut Line= 3
     1735400.254      118924.663     1735212.204      119390.023
     1735071.951      119747.015
#Sta/Elev= 30
      10 1724.91    30.1 1718.16    40.2 1715.52    70.3 1710.93    80.3 1708.65
   100.4 1700.35   120.5 1688.88   170.7 1654.49   220.8 1623.08   281.1 1582.03
   321.2 1556.56   341.3 1545.23   391.5 1519.34   421.6 1502.12   489.4 1473.82
   491.9 1472.88   501.9 1471.62     512 1474.11   514.4 1475.41   532.2  1485.1
   542.3 1488.67   552.4 1491.58   572.6 1495.87     623 1501.48   633.1 1504.07
   653.3 1510.88   663.4 1513.15   774.4 1529.18   824.9 1538.07   885.5 1546.66
#Mann= 3 , 0 , 0
       0      .1       0   489.4    .045       0   514.4      .1       0
Bank Sta=489.4,514.4
XS Rating Curve= 0 ,0
Exp/Cntr=0.3,0.1

Type RM Length L Ch R = 1 ,5951.5  ,348.7,342.4,335.8
XS GIS Cut Line= 4
     1735142.074      118819.478     1734947.641      119023.472
      1734568.34      119201.967     1734491.842      119523.896
#Sta/Elev= 30
    10.1 1663.65    50.3 1650.21    80.5 1637.37   191.2 1579.05   281.8 1537.36
   341.7 1505.61   391.6 1482.42   421.5 1471.87   498.9 1459.71   511.4 1458.44
   521.4 1460.56   523.9 1461.89   581.2 1495.18   601.2 1504.42   621.2 1509.69
   671.1 1520.42     701 1528.18   781.2 1545.85   811.3 1554.73   831.4 1563.39
   871.5 1583.63   881.5 1587.21   891.5  1589.5   901.6 1594.18   931.6 1613.44
   941.7 1618.23   961.7 1624.42   971.7 1629.11  1001.8 1646.04  1031.9 1661.59
#Mann= 3 , 0 , 0
    10.1      .1       0   498.9    .045       0   523.9      .1       0
#XS Ineff= 2 , 0
          492.41    1473
Permanent Ineff=
       F       F
Bank Sta=498.9,523.9
XS Rating Curve= 0 ,0
Exp/Cntr=0.3,0.1

Type RM Length L Ch R = 1 ,5609.2  ,320,325,330.2
XS GIS Cut Line= 3
     1735017.765      118526.236      1734675.67      118789.297
     1734268.723       119112.72
#Sta/Elev= 30
      10 1679.52    40.1 1668.35    60.2 1660.01   100.4 1641.51   130.5 1626.55
   160.6 1609.91   180.6 1598.02   210.8 1579.24   260.9 1547.15   361.3 1491.25
   411.5 1465.16   431.5 1453.05     439 1450.72   441.5 1449.94   451.5 1449.19
     464 1449.38   521.5 1450.54   531.5  1451.1   541.5  1452.4   621.5 1467.25
   631.5 1469.77   641.5 1473.29   651.5 1477.87   681.5 1493.28   711.4 1510.19
   741.4 1528.41   811.4 1572.76   851.4 1596.11   901.4 1622.73   951.4  1646.8
#Mann= 3 , 0 , 0
      10      .1       0     439    .045       0     464     .08       0
#XS Ineff= 2 , 0
                          519.75          1573.8
Permanent Ineff=
       F       F
Bank Sta=439,464
XS Rating Curve= 0 ,0
Exp/Cntr=0.3,0.1

Type RM Length L Ch R = 1 ,5284.1  ,252.3,231.9,211.5
XS GIS Cut Line= 4
     1734683.086      118248.932     1734520.187      118536.286
      1734297.41      118653.733     1734173.101      118997.973
#Sta/Elev= 30
      10 1701.08      40 1672.31    70.1 1641.35    80.1 1632.41    90.1 1625.27
   190.2 1565.93   230.2 1543.27   250.2 1532.66   310.3 1504.35   330.3 1494.11
   350.5 1482.79   370.6 1470.61   380.7 1463.49   400.8 1445.98   408.5 1442.81
   410.9 1441.83     421 1441.46   433.5 1442.54   511.6  1448.2     562 1453.75
   572.1 1455.98   601.9 1465.69   641.5 1479.14   661.3  1486.8   681.1 1496.63
     691 1502.33   720.6 1520.98     780 1556.32   888.8 1623.25   948.2  1655.6
#Mann= 3 , 0 , 0
       0      .1       0   408.5    .045       0   433.5      .1       0
Bank Sta=408.5,433.5
XS Rating Curve= 0 ,0
Exp/Cntr=0.3,0.1

Type RM Length L Ch R = 1 ,5052.3  ,357.9,366.6,375.7
XS GIS Cut Line= 3
     1734401.874      118060.347     1734249.777      118480.225
     1734122.226       118877.78
#Sta/Elev= 30
     9.9 1699.84    19.8 1688.92    39.7 1662.49    49.6 1650.67    59.5 1640.37
    79.4 1622.27    99.2 1605.57     129 1583.15   148.9 1572.43   238.2 1529.61
   248.1 1525.23   267.9 1518.79   287.8 1509.85   297.7 1503.56   307.6 1495.89
   337.4 1467.67   347.3 1458.72   357.3 1450.84   367.2 1445.28   394.4 1437.15
   406.9 1434.74   419.4  1435.6   565.9    1468   655.3 1494.07   675.2 1503.09
   695.1 1513.56   744.8 1543.75   774.6 1560.55   834.3 1591.03   864.1 1605.13
#Mann= 3 , 0 , 0
       0      .1       0   394.4    .045       0   419.4      .1       0
Bank Sta=394.4,419.4
XS Rating Curve= 0 ,0
Exp/Cntr=0.3,0.1

Type RM Length L Ch R = 1 ,4685.7  ,435.6,450,461.9
XS GIS Cut Line= 3
     1734249.079      117887.735     1733975.914      118251.048
      1733695.26      118612.579
#Sta/Elev= 30
    10.1  1662.8    40.4 1652.46    70.7 1629.26   111.1 1591.68   151.5 1559.89
     202 1526.89   232.3 1509.98   262.6 1495.09   282.8 1483.33   313.1  1460.1
   323.2 1453.52   333.3 1448.28   343.4 1445.47   353.5 1443.78   383.8 1442.02
   393.9  1439.7   424.2  1427.7     442 1423.44   454.5 1422.65     467 1425.41
   494.3 1435.96   633.6 1481.84   723.2 1513.52     753  1526.6   782.9 1541.97
   842.6 1579.11   862.5 1590.33   872.4 1594.02   892.3 1596.13   912.2  1602.5
#Mann= 3 , 0 , 0
       0     .08       0     442    .045       0     467     .08       0
Bank Sta=442,467
XS Rating Curve= 0 ,0
Exp/Cntr=0.3,0.1

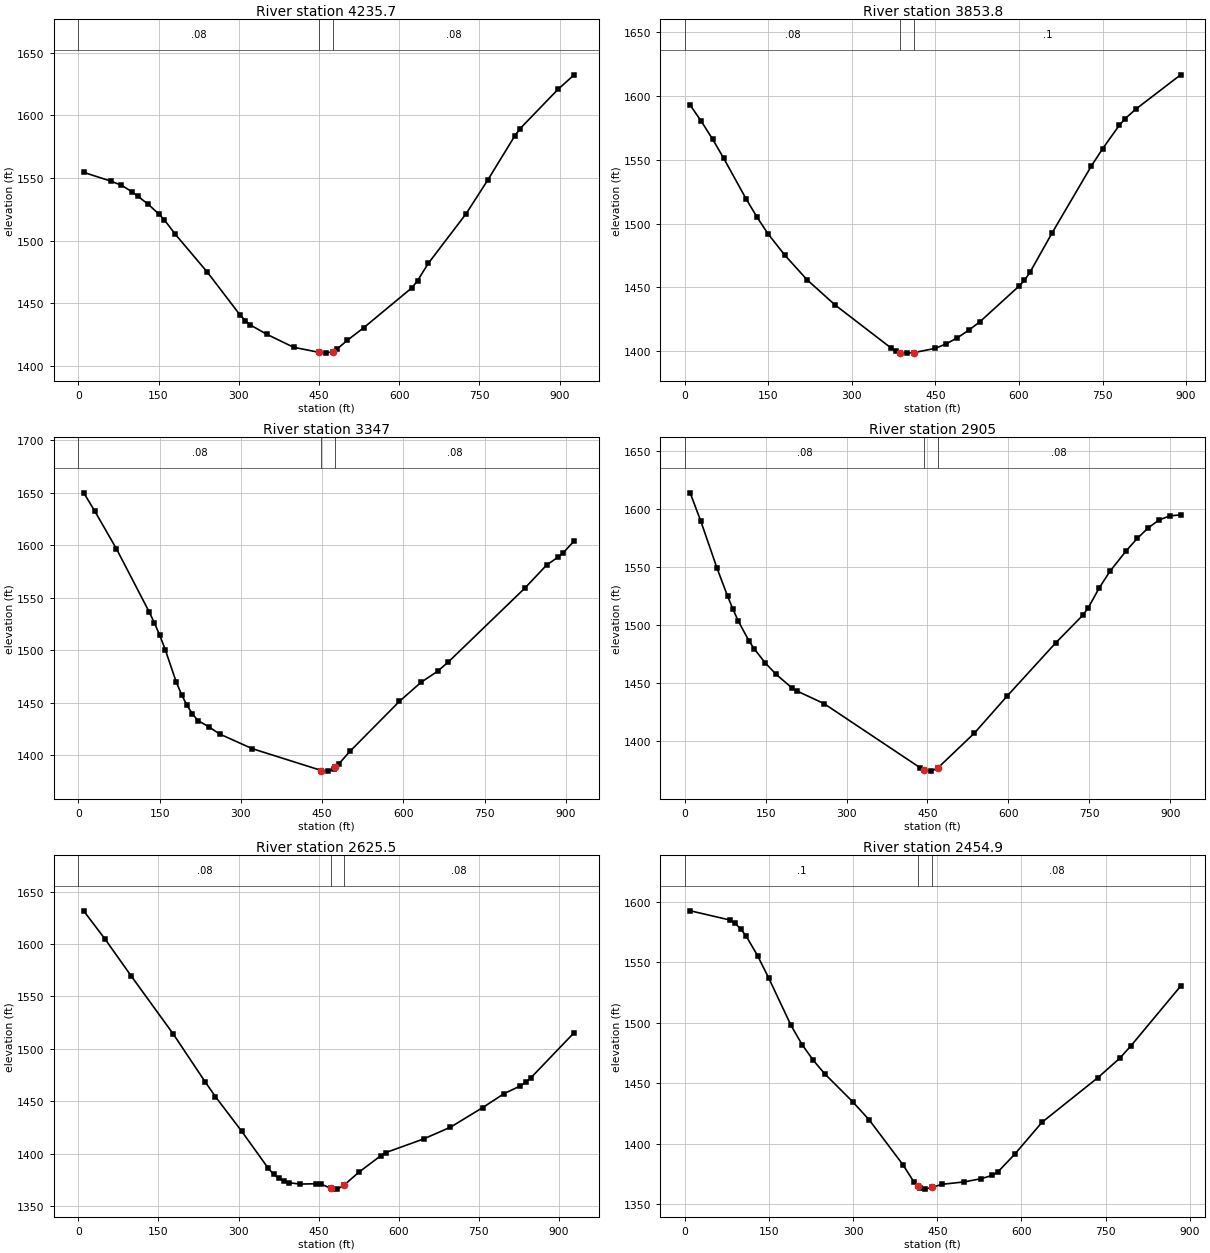
Type RM Length L Ch R = 1 ,4235.7  ,397.1,381.9,365.9
XS GIS Cut Line= 3
     1734097.663      117748.069     1733689.085      117943.081
     1733277.438      118178.809
#Sta/Elev= 30
    10.1 1554.49    60.4 1547.55    80.5 1544.22   100.6 1538.93   110.7 1535.62
   130.8 1528.95   150.9 1521.09     161 1516.44   181.1 1505.13   241.5  1474.6
   301.8 1440.84   311.9 1436.11   321.9 1432.48   352.1 1425.16   402.4 1414.73
   450.3 1410.65   462.8 1410.04   475.3  1411.2     483 1413.03   503.2 1420.36
   533.5  1430.3   624.3 1462.48   634.4 1468.08   654.6 1481.91   725.2 1521.53
   765.6 1548.38   816.1 1583.65   826.2 1589.54   896.8 1620.82   927.1 1632.45
#Mann= 3 , 0 , 0
       0     .08       0   450.3    .045       0   475.3     .08       0
Bank Sta=450.3,475.3
XS Rating Curve= 0 ,0
Exp/Cntr=0.3,0.1

Type RM Length L Ch R = 1 ,3853.8  ,529.6,506.8,487.9
XS GIS Cut Line= 3
     1733628.054      117381.956     1733410.787      117705.027
     1733169.066      118143.747
#Sta/Elev= 30
      10 1592.63    29.9 1580.02    49.9 1566.16    69.9 1551.17   109.8 1519.57
   129.8 1504.98   149.7 1491.83   179.7 1475.19   219.6 1455.95   269.5 1436.35
   369.4 1402.83   379.3 1399.95   386.8 1398.96   399.4  1398.5   411.8 1398.95
   449.4 1402.19   469.5 1405.77   489.5 1410.59   509.5 1416.34   529.6 1422.99
   599.7 1450.86   609.7 1455.48   619.7 1461.83   659.8 1492.96   729.9 1545.11
     750 1558.58     780 1576.99   790.1 1582.03   810.1 1589.81   890.2 1616.58
#Mann= 3 , 0 , 0
       0     .08       0   386.8    .045       0   411.8      .1       0
Bank Sta=386.8,411.8
XS Rating Curve= 0 ,0
Exp/Cntr=0.3,0.1

Type RM Length L Ch R = 1 ,3347    ,436.6,442,446.6
XS GIS Cut Line= 3
     1732835.714      117333.195     1732939.234      117782.688
     1733025.626      118228.286
#Sta/Elev= 30
      10 1649.96    30.1 1632.76    70.2 1596.77   130.4 1536.88   140.4 1525.96
   150.4 1514.12   160.4 1500.61   180.5 1470.02   190.5 1457.76   200.5 1447.54
   210.6 1439.38   220.6 1433.03   240.7 1427.07   260.7 1420.19   320.9 1406.22
   448.8 1385.39   461.3  1384.8   471.3 1387.02   473.8 1388.26   481.4 1392.04
   501.6 1403.78   592.4 1451.15   632.7 1469.47     663  1479.9   683.2  1488.9
   824.4 1559.26   864.7 1581.33   884.9 1588.44     895 1592.86   915.2 1604.08
#Mann= 3 , 0 , 0
       0     .08       0   448.8    .045       0   473.8     .08       0
Bank Sta=448.8,473.8
XS Rating Curve= 0 ,0
Exp/Cntr=0.3,0.1

Type RM Length L Ch R = 1 ,2905    ,277.7,279.5,281.1
XS GIS Cut Line= 3
     1732487.912      117359.041     1732502.037      117825.277
     1732511.467      118278.111
#Sta/Elev= 30
     9.9 1614.02    29.8 1589.44    59.5  1549.4    79.4 1524.86    89.3 1513.69
    99.2 1503.45   119.1 1486.22     129 1479.35   148.9 1467.53   168.7 1457.78
   198.5  1445.9   208.4 1443.08     258 1432.34   436.7 1376.91     444 1375.29
   456.5 1374.09     469 1376.72   536.9 1406.83   597.3 1438.59   687.9 1484.73
   738.2 1508.58   748.3 1515.08   768.4 1531.99   788.5 1546.47   818.7 1564.13
   838.9 1574.68     859 1583.64   879.1 1590.55   899.3 1594.13   919.4 1595.04
#Mann= 3 , 0 , 0
       0     .08       0     444    .045       0     469     .08       0
Bank Sta=444,469
XS Rating Curve= 0 ,0
Exp/Cntr=0.3,0.1

Type RM Length L Ch R = 1 ,2625.5  ,172,170.6,169.2
XS GIS Cut Line= 3
     1732142.546      117310.969      1732228.78      117716.634
     1732209.656      118229.807
#Sta/Elev= 30
     9.9 1631.68    49.4 1605.16    98.7 1569.74   177.7 1514.23     237 1468.93
   256.7 1454.47   306.1 1421.31   355.5 1386.24   365.4 1380.44   375.2 1376.56
   385.1 1374.08     395 1372.38   414.7 1371.11   444.9 1371.43     455 1370.95
   472.7 1367.09   475.1 1366.54   485.2  1366.3   497.7  1370.2   525.5 1382.56
   565.8 1397.95   575.8 1401.16   646.3 1414.12   696.7 1425.34   757.1 1444.07
   797.4 1457.47   827.6 1464.72   837.6 1468.06   847.7 1472.69   928.3  1515.5
#Mann= 3 , 0 , 0
       0     .08       0   472.7    .045       0   497.7     .08       0
Bank Sta=472.7,497.7
XS Rating Curve= 0 ,0
Exp/Cntr=0.3,0.1

Type RM Length L Ch R = 1 ,2454.9  ,102.7,99.8,96.8
XS GIS Cut Line= 4
     1732043.911      117334.145      1732056.66      117652.886
     1732059.848      117891.942     1732078.972      118217.058
#Sta/Elev= 30
      10 1592.52    79.7 1584.99    89.7 1582.12    99.7 1577.56   109.7 1571.36
   129.6 1555.54   149.5 1537.03   189.4  1497.7   209.3 1481.71   229.3 1468.79
   249.2 1457.86   299.1 1434.73     329 1419.48   388.7 1382.64   408.6 1368.19
   416.1 1364.59   418.6 1363.38   428.6  1362.4   441.1 1363.92   458.5 1366.41
   498.3 1368.37   528.2 1371.05   548.1 1373.74   558.1 1376.62   587.7 1391.08
     637 1417.79   735.7 1454.33   775.2 1470.58   794.9 1480.71   883.8 1530.25
#Mann= 3 , 0 , 0
       0      .1       0   416.1    .045       0   441.1     .08       0
Bank Sta=416.1,441.1
XS Rating Curve= 0 ,0
Exp/Cntr=0.3,0.1

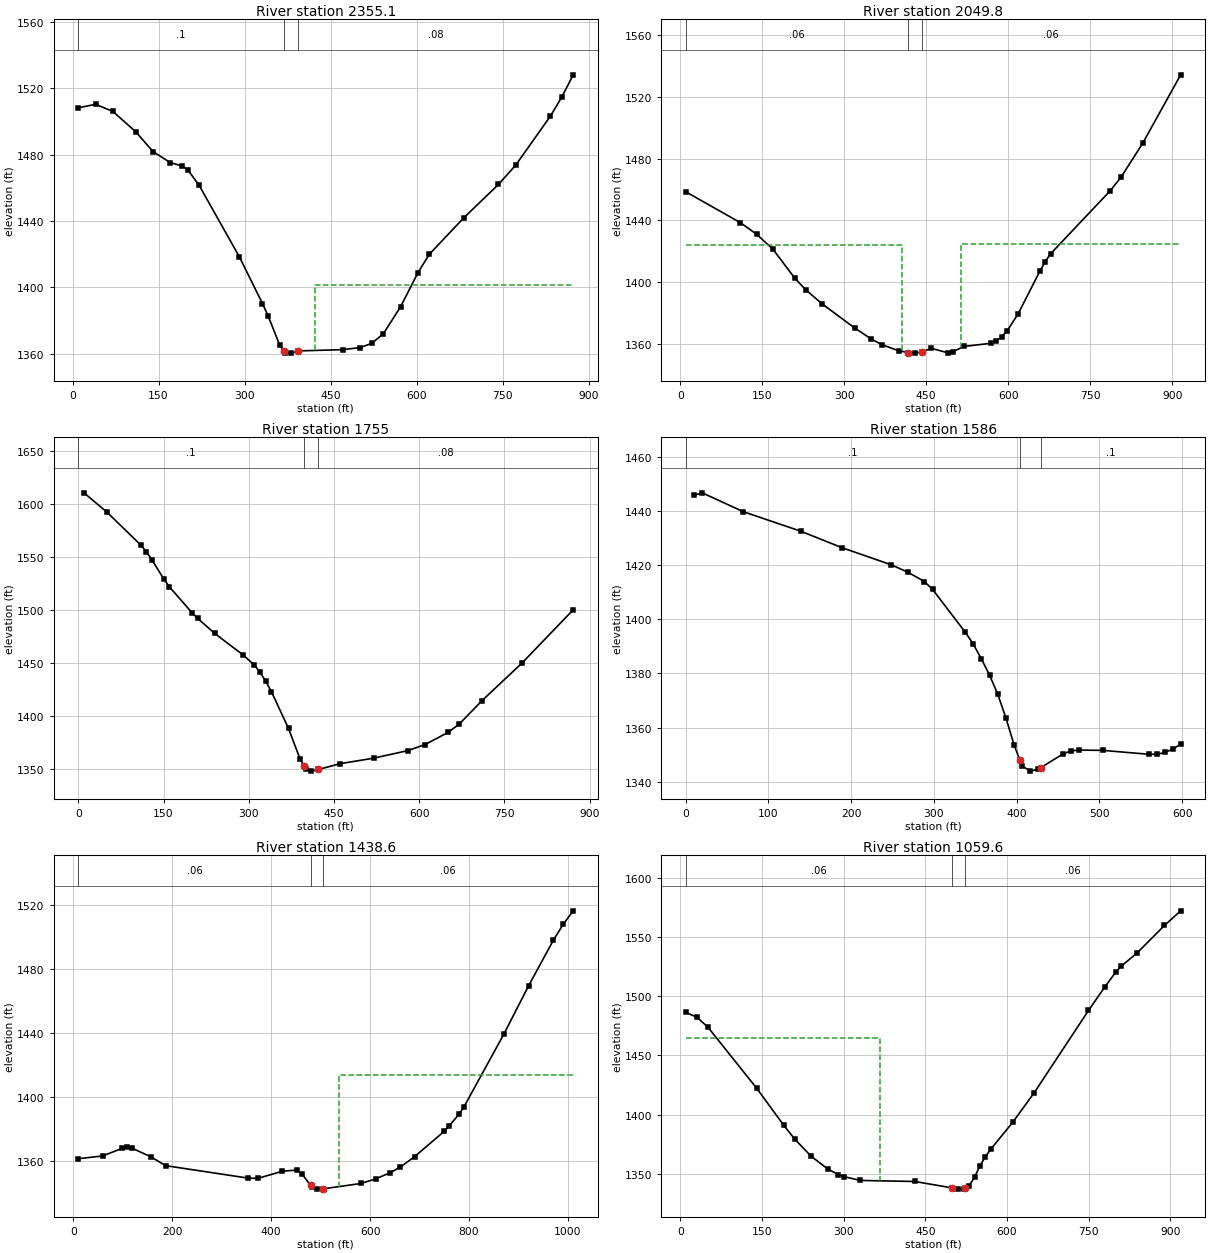
Type RM Length L Ch R = 1 ,2355.1  ,317.5,305.3,294
XS GIS Cut Line= 2
     1731913.227      117375.581     1732018.411      118242.557
#Sta/Elev= 30
      10 1508.22    40.2  1510.3    70.3 1506.03   110.4 1493.72   140.5 1481.78
   170.7 1475.15   190.7 1473.17   200.8 1470.94   220.8 1461.47   291.1 1418.32
   331.3 1390.23   341.3 1382.65   361.4  1365.1     369 1361.78   371.4 1360.73
   381.5 1360.37     394 1361.71   471.8 1362.47   501.9 1363.73     522 1366.28
   542.1 1372.04   572.2 1388.32   602.3 1408.79   622.4 1419.99   682.6 1441.98
   742.8 1462.01   772.9 1473.65   833.2 1503.04   853.3  1514.7   873.3 1528.09
#Mann= 3 , 0 , 0
      10      .1       0     369    .045       0     394     .08       0
#XS Ineff= 2 , 0
                          423.09         1401.68
Permanent Ineff=
       F       F
Bank Sta=369,394
XS Rating Curve= 0 ,0
Exp/Cntr=0.3,0.1

Type RM Length L Ch R = 1 ,2049.8  ,291,294.8,297.8
XS GIS Cut Line= 3
     1731457.427      117483.953     1731700.032      117885.682
     1731913.227      118277.618
#Sta/Elev= 30
      10  1458.5   109.8  1438.5   139.8 1430.95   169.7  1421.2   209.7 1402.39
   229.7 1394.93   259.6 1385.82   319.5  1370.1   349.5 1363.07   369.4 1359.32
   399.4 1355.48   416.9  1354.3   429.4 1353.92   441.9 1354.65   459.3 1357.04
   489.1 1354.15     499 1354.87   518.9 1358.24   568.4 1360.31   578.4 1361.84
   588.3 1364.64   598.2 1368.44     618 1379.31   657.7  1406.9   667.6 1413.16
   677.5 1418.29   786.6 1459.14   806.4 1467.94   846.1 1489.97   915.5 1534.27
#Mann= 3 , 0 , 0
      10     .06       0   416.9    .045       0   441.9     .06       0
#XS Ineff= 2 , 0
          406.37  1423.8  513.38         1424.54
Permanent Ineff=
       F       F
Bank Sta=416.9,441.9
XS Rating Curve= 0 ,0
Exp/Cntr=0.3,0.1

Type RM Length L Ch R = 1 ,1755    ,180.8,169,157.2
XS GIS Cut Line= 4
     1731211.996      117614.637     1731387.304      117882.379
     1731463.802      118067.249     1731686.921      118338.179
#Sta/Elev= 30
      10 1610.79      50 1592.76     110 1561.49     120    1555     130 1547.17
     150 1529.87     160 1522.25     200 1497.69     210 1492.28     240 1478.08
     290 1457.72     310  1448.1     320 1441.18     330 1432.82     340 1422.93
     370 1388.27   390.1 1359.81   397.6 1352.76   400.1  1350.4   410.1 1348.01
   422.6 1349.55   460.1 1354.97   520.1 1360.27   580.3  1367.4   610.4 1373.12
   650.5 1384.49   670.5 1392.44   710.6  1414.6   780.8 1449.99   871.1 1500.36
#Mann= 3 , 0 , 0
       0      .1       0   397.6    .045       0   422.6     .08       0
Bank Sta=397.6,422.6
XS Rating Curve= 0 ,0
Exp/Cntr=0.3,0.1

Type RM Length L Ch R = 1 ,1586    ,165.2,147.4,128.8
XS GIS Cut Line= 4
     1730972.941      117745.321     1731176.935      117949.315
     1731310.806      118079.999     1731431.928      118060.874
#Sta/Elev= 30
     9.9 1445.69    19.9 1446.62    69.6 1439.66   139.3 1432.44     189 1426.37
   248.7 1420.05   268.6 1417.32   288.5 1413.91   298.3 1411.02   337.7 1395.28
   347.6 1390.83   357.4 1385.35   367.3 1379.35   377.1 1372.36     387 1363.59
   396.8 1353.73     404 1347.96   406.6 1345.88   416.5 1343.99   426.3 1344.77
     429 1345.26   455.9  1350.3   465.7 1351.48   475.6 1351.74   503.9 1351.65
   560.5 1350.18   569.9 1350.23   579.3 1350.88   588.8 1352.17   598.2 1353.89
#Mann= 3 , 0 , 0
       0      .1       0     404    .045       0     429      .1       0
Bank Sta=404,429
XS Rating Curve= 0 ,0
Exp/Cntr=0.3,0.1

Type RM Length L Ch R = 1 ,1438.6  ,360.7,379,397.9
XS GIS Cut Line= 4
     1730816.758      117946.128     1731065.376      118137.372
     1731498.863      118185.183     1731641.267      118404.077
#Sta/Elev= 30
     9.8 1361.14    58.8 1362.85      98 1367.56   107.8 1368.19   117.6 1367.87
   156.8  1362.3   186.2 1356.79   353.3 1348.97   373.1  1348.8   422.7  1353.3
   452.4 1354.03   462.3  1351.6   479.6 1344.41   482.2 1343.44   492.1 1342.07
   504.6 1342.23   581.3  1345.6     611 1348.44   640.8  1352.4   660.6 1355.77
   690.3 1362.48   749.8 1378.27   759.8 1381.62   779.9 1389.05     790  1393.7
   870.3 1439.04   920.5 1469.44   970.7 1498.06   990.8 1508.13  1010.9 1516.48
#Mann= 3 , 0 , 0
     9.8     .06       0   479.6    .045       0   504.6     .06       0
#XS Ineff= 2 , 0
                          536.56         1413.73
Permanent Ineff=
       F       F
Bank Sta=479.6,504.6
XS Rating Curve= 0 ,0
Exp/Cntr=0.3,0.1

Type RM Length L Ch R = 1 ,1059.6  ,585.8,596.5,606.7
XS GIS Cut Line= 3
      1730676.91      118122.232     1731047.833      118458.771
      1731350.25      118747.761
#Sta/Elev= 30
      10 1486.41    30.1 1482.41    50.1 1474.28   140.2 1422.37   190.3 1390.79
   210.4 1379.17   240.4 1364.75   270.5 1354.13   290.5  1349.2   300.5 1347.55
   330.6 1344.32   430.7 1343.43   498.3 1338.09   510.8 1336.97   520.8 1337.05
   523.3 1337.78   530.7 1339.94   540.7 1347.31   550.6 1356.87   560.6 1364.52
   570.6 1370.92   610.4 1393.34   650.2 1418.55   749.8 1488.03   779.7 1507.92
   799.6 1520.26   809.6 1525.32   839.5 1536.86   889.3 1559.92   919.1  1572.3
#Mann= 3 , 0 , 0
      10     .06       0   498.3    .045       0   523.3     .06       0
#XS Ineff= 2 , 0
          366.88 1464.94
Permanent Ineff=
       F       F
Bank Sta=498.3,523.3
XS Rating Curve= 0 ,0
Exp/Cntr=0.3,0.1

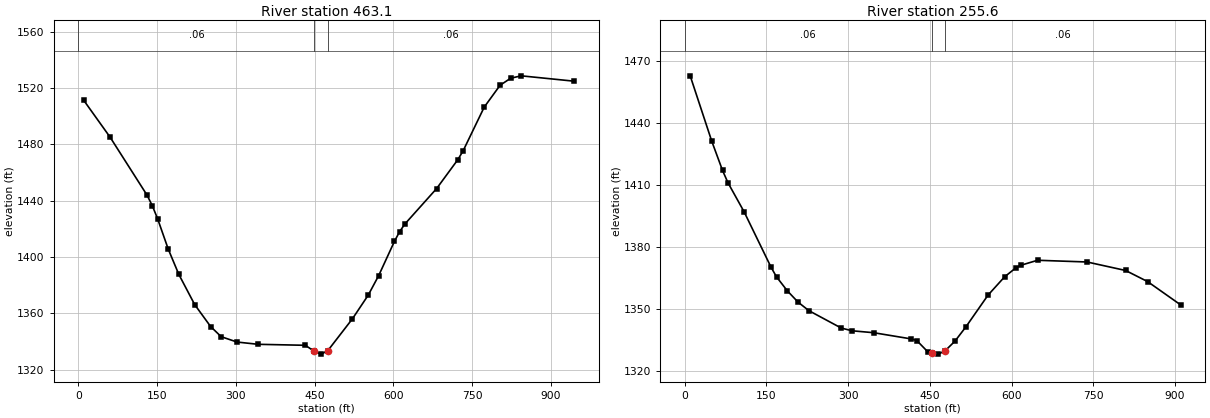
Type RM Length L Ch R = 1 ,463.1   ,207.8,207.5,205.8
XS GIS Cut Line= 4
      1730370.52      118220.245     1730440.643      118545.361
     1730564.952      118806.728     1730796.778      119030.906
#Sta/Elev= 30
    10.1  1511.4    60.5 1485.13     131  1443.9   141.1 1436.33   151.2 1427.03
   171.3 1405.63   191.5 1387.65   221.7 1366.24     252  1350.7   272.1 1343.49
   302.4 1339.68   342.6 1338.08   432.4 1337.38   449.8 1333.05   462.3 1331.11
   474.8 1333.37   522.2 1356.23   552.2 1372.99   572.1 1386.83   602.1 1411.12
     612 1418.06     622 1423.47   682.5 1448.66   722.8 1469.12   732.9 1475.38
   773.2 1506.48   803.4    1522   823.6    1527   843.7 1528.69   944.5 1524.88
#Mann= 3 , 0 , 0
       0     .06       0   449.8    .045       0   474.8     .06       0
Bank Sta=449.8,474.8
XS Rating Curve= 0 ,0
Exp/Cntr=0.3,0.1

Type RM Length L Ch R = 1 ,255.6   ,253.3,250.6,249.5
XS GIS Cut Line= 3
     1730110.439      118343.715     1730309.947      118753.432
     1730530.679      119150.974
#Sta/Elev= 30
     9.9 1462.91    49.5 1431.21    69.3 1417.02    79.3 1411.05     109 1396.92
   158.5 1370.03   168.4 1365.43   188.2 1358.67     208 1353.16   227.9 1349.03
   287.3  1340.6   307.1 1339.28   346.7 1338.35   416.1 1335.32     426 1334.54
   445.8 1329.18   453.3  1328.3   465.8 1327.96   478.3 1329.66   496.1 1334.27
   516.3 1341.24   556.8 1356.58   587.1 1365.42   607.3 1369.68   617.4 1371.08
   647.7 1373.47   738.6 1372.64   809.4 1368.52   849.8 1363.13   910.4 1351.85
#Mann= 3 , 0 , 0
       0     .06       0   453.3    .045       0   478.3     .06       0
Bank Sta=453.3,478.3
XS Rating Curve= 0 ,0
Exp/Cntr=0.3,0.1