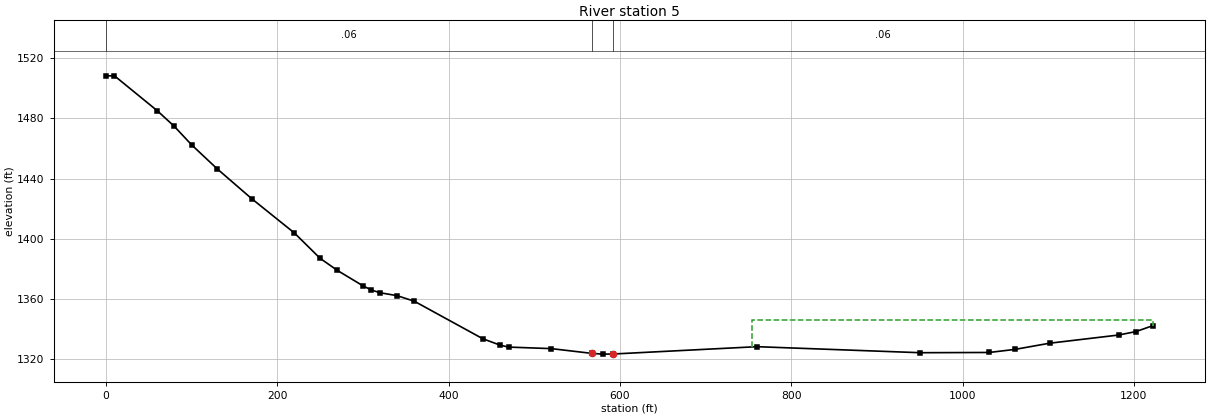
HEC-RAS study Hite Fork.prj: Hite Fork

--- Hite Fork.g01 (geometry) --- (continued)

Type RM Length L Ch R = 1 ,5       ,12.5,5,0
XS GIS Cut Line= 4
     1730011.846      118307.595     1730033.545      118777.116
     1730233.585      119100.037     1730590.798      119205.772
#Sta/Elev= 30
       0 1508.16      10 1508.16      60 1484.99      80 1474.56     100 1462.41
     130 1446.42     170 1426.76     220 1403.94     250 1387.13     270 1379.15
     300 1368.89     310 1366.05     320 1364.28     340 1362.32     360 1358.65
     440 1333.75     460 1329.55     470 1328.22     520  1327.2   567.5 1324.03
     580 1323.55   592.5 1323.64   759.9 1328.49   950.6 1324.49  1031.1 1324.65
  1061.3  1326.7  1101.6 1330.79  1182.1 1336.21  1202.3 1338.49  1222.4 1342.49
#Mann= 3 , 0 , 0
       0     .06       0   567.5    .045       0   592.5     .06       0
#XS Ineff= 2 , 0
                          753.82         1346.44
Permanent Ineff=
       F       F
Bank Sta=567.5,592.5
XS Rating Curve= 0 ,0
Exp/Cntr=0.3,0.1
Stream Node=Hite Fork       ,Main            , 0 , 0 ,Upstream end
Stream Node=Hite Fork       ,Main            , 0 , 1 ,Downstream end

Chan Stop Cuts=-1
Use User Specified Reach Order=0